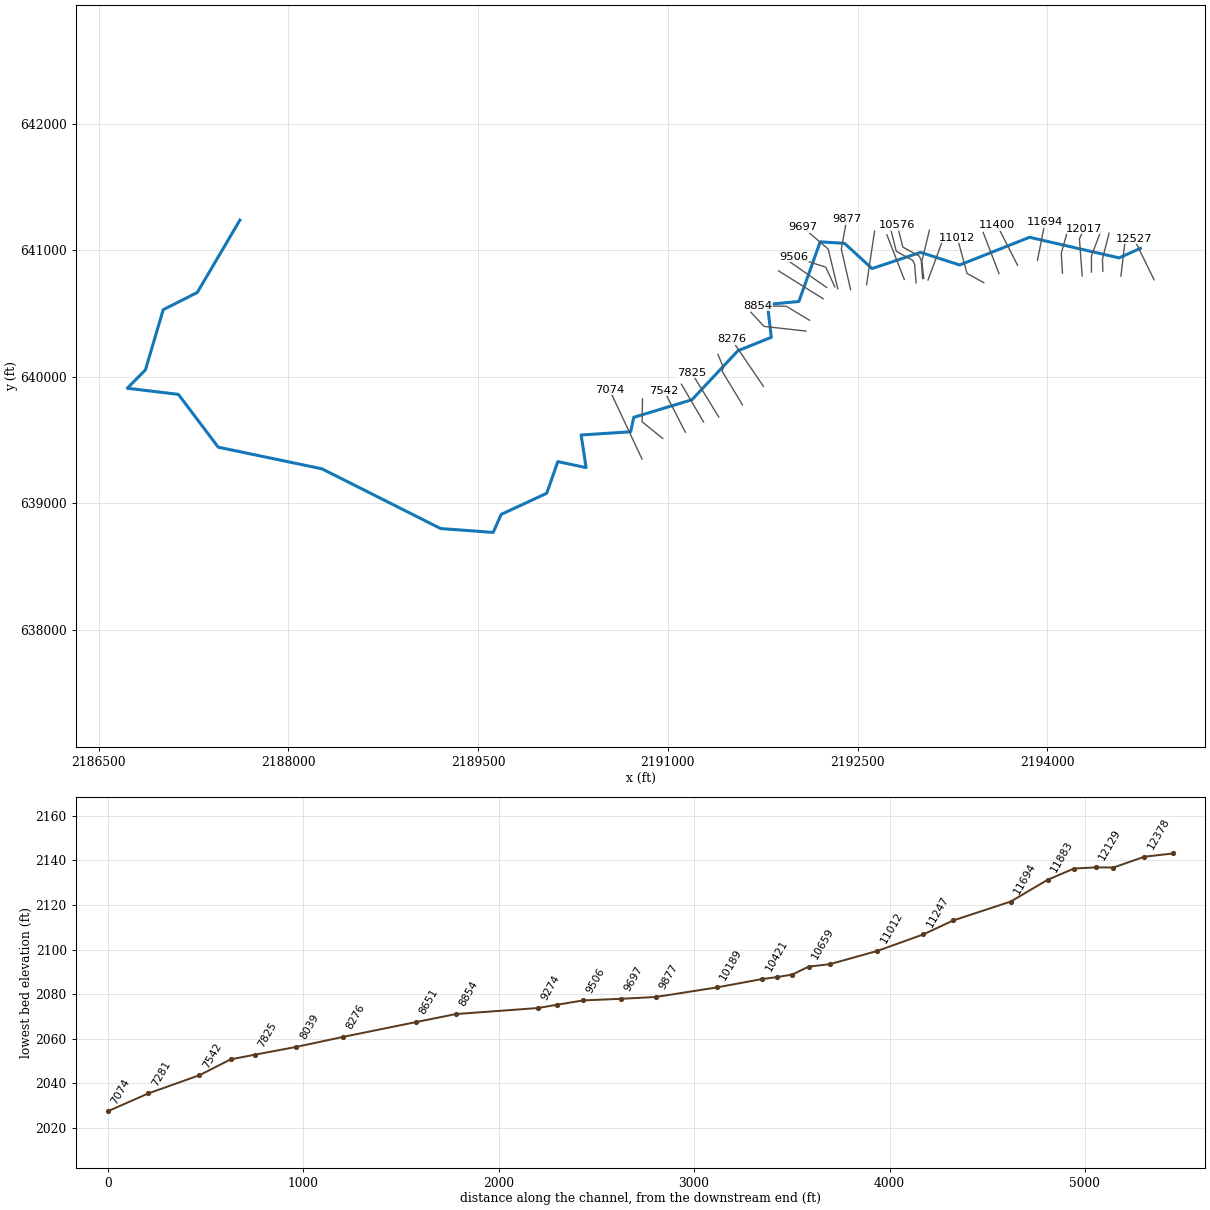
--- MILLSITERN.prj (project) ---

Proj Title=MILLSITERN
Current Plan=p01
Default Exp/Contr=0,0
English Units
Geom File=g01
Flow File=f01
Plan File=p01
BEGIN DESCRIPTION:
----------MODELED AS PART OF WVEMD CTP PROGRAM, 2022---------
AFH study
Upshur County, WV
HEC-RAS Version: RAS 6.3
Vertical Datum: NAVD88
Projection: NAD 1983 StatePlane West Virginia S FIPS 4702 (US Feet)
Terrain: 1-meter LIDAR (FEMA Region III 3DEP collected 2016-2018)
Land Use: 2019 NLCD
Hydrologic Method:
WV 2010 Regional Regression Equations
Additional Model Notes:
None
END DESCRIPTION:
DSS Export Rating Curves= 0
DSS Export Rating Curve Sorted= 0
DSS Export Volume Flow Curves= 0
DXF OffsetX= 0
DXF OffsetY= 0
DXF ScaleX= 0
DXF ScaleY= 0

--- MILLSITERN.p01 (plan) ---

Plan Title=Floodplain
Program Version=6.31
Short Identifier=Floodplain
Geom File=g01
Flow File=f01
Subcritical Flow
K Sum by GR= 0
Std Step Tol= 0.01
Critical Tol= 0.01
Num of Std Step Trials= 20
Max Error Tol= 0.3
Flow Tol Ratio= 0.001
Split Flow NTrial= 30
Split Flow Tol= 0.02
Split Flow Ratio= 0.02
Log Output Level= 0
Friction Slope Method= 1
Unsteady Friction Slope Method= 2
Unsteady Bridges Friction Slope Method= 1
Parabolic Critical Depth
Global Vel Dist= 0 , 0 , 0
Global Log Level= 0
CheckData=True
Encroach Param=-1 ,0,0, 0
Mapping Interval=1HOUR
Computation Time Step Use Courant=        0
Computation Time Step Use Time Series=    0
Computation Time Step Count To Double=0
Computation Time Step Max Doubling=0
Computation Time Step Max Halving=0
Computation Time Step Residence Courant=0
Run HTab= 0
Run UNet= 0
Run Sediment= 0
Run PostProcess= 0
Run WQNet= 0
Run RASMapper=-1
UNET Theta= 0
UNET Theta Warmup= 0
UNET ZTol= 0
UNET ZSATol= 0
UNET MxIter= 0
UNET Max Iter WO Improvement= 0
UNET MaxInSteps= 0
UNET DtIC= 0
UNET DtMin= 0
UNET MaxCRTS= 0
UNET WFStab= 0
UNET SFStab= 0
UNET WFX= 1
UNET SFX= 1
UNET Gravity=32.17405
UNET 1D Methodology=Finite Difference
UNET DSS MLevel= 1
UNET Pardiso=0
UNET DZMax Abort= 0
UNET Use Existing IB Tables= 0
UNET Froude Reduction=False
UNET Froude Limit= 0
UNET Froude Power= 0
UNET D1 Cores= 0
UNET WindReference=Eulerian
UNET WindDragFormulation=Hsu (1988)
UNET D2 Coriolis=0
UNET D2 Cores= 0
UNET D2 Theta= 1
UNET D2 Theta Warmup= 1
UNET D2 Z Tol= 0.01
UNET D2 Volume Tol= 0.01
UNET D2 Max Iterations= 20
UNET D2 Equation= 0
UNET D2 RampUpFraction=0.1
UNET D2 TimeSlices= 1
UNET D2 Turbulence Formulation=Non-Conservative (original)
UNET D2 Eddy Viscosity=0.3
UNET D2 Transverse Eddy Viscosity=0.1
UNET D2 Smagorinsky Mixing=0
UNET D2 BCVolumeCheck=0
UNET D2 Cores=0
UNET D2 SolverType=PARDISO (Direct)
UNET D2 Minimum Iterations= 3
UNET D2 Maximum Iterations= 30
UNET D2 Restart Number= 10
UNET D2 Relaxation Coeff=1.3
UNET D2 SOR Precondition Iterations= 10
UNET D2 ILUT Maximum Fill= 8
UNET D2 ILUT Tolerance=1E-08
UNET D2 Convergence Tolerance=0.00001
UNET D1D2 MaxIter= 0
UNET D1D2 ZTol=0.01
UNET D1D2 QTol=0.1
UNET D1D2 MinQTol=1
Write IC File= 0
Write IC File at Fixed DateTime=0
Write IC File at Sim End=0
Echo Input=False
Echo Parameters=False
Echo Output=False
Write Detailed= 0
HDF Write Warmup=0
HDF Write Time Slices=0
HDF Flush=0
HDF Compression= 1
HDF Chunk Size= 1
HDF Spatial Parts= 1
HDF Use Max Rows=0
HDF Fixed Rows= 1
Calibration Method= 0
Calibration Iterations= 20
Calibration Max Change=0.05
Calibration Tolerance=0.2
Calibration Maximum=1.5
Calibration Minimum=0.5
Calibration Optimization Method= 1
WQ AD Non Conservative
WQ ULTIMATE=-1
WQ Max Comp Step=1HOUR
WQ Output Interval=15MIN
WQ Output Selected Increments= 0
WQ Create Restart=0
WQ Fixed Restart=0
WQ System Summary=0
WQ Write To DSS=0
Sorting and Armoring Iterations= 10
XS Update Threshold= 0.02
Bed Roughness Predictor= 0
Hydraulics Update Threshold= 0.02
Energy Slope Method= 1
Volume Change Method= 1
Sediment Retention Method= 0
Sediment TS Multiplier= 1
Warm Up Method= 0
XS Weighting Method= 0
Number of US Weighted Cross Sections= 1
Number of DS Weighted Cross Sections= 1
Upstream XS Weight=0
Main XS Weight=1
Downstream XS Weight=0
Number of DS XS's Weighted with US Boundary= 1
Upstream Boundary Weight= 1
Weight of XSs Associated with US Boundary= 0
Number of US XS's Weighted with DS Boundary= 1
Downstream Boundary Weight= 0.5
Weight of XSs Associated with DS Boundary= 0.5
Percentile Method= 0
Sediment Output Level= 3
Mass or Volume Output= 0
Output Increment Type= 1
Profile and TS Output Increment= 1
Transport Output Increment 1
XS Output Flag= 0
XS Output Increment= 10
Read HDF5 Sediment Hotstart= 0
Sediment Hotstart Type= 0
Write Gradation File= 0
Read Gradation Hotstart= 0
Write HDF5 File= 1
Write Binary Output= 1
Write DSS Sediment File= 0
DSS Sediment Output Type= 1
SV Curve= 0
Specific Gage Flag= 0
Subcell Erosion Methods= 0
Subcell Deposition Methods= 0
Advection Scheme= 1
Matrix Solver= 0
Implicit Weighting Factor= 1
Maximum Outer Loop Convergence Iterations= 5
Convergence Maximum Absolute= 0.001
Convergence RMSE= 0.0001
Grain Fractions Max Abs Error= 0.001
Max Subgrid Regions= 1
Max Subgrid Length Scale= 3.402823E+38
Initial Layer Thickness= 3.402823E+38
Min Layer Thickness= 3.402823E+38
Max Layer Thickness= 3.402823E+38
Number of Layers= 5

--- MILLSITERN.f01 (steady flow) ---

Flow Title=Flows
Program Version=6.31
Number of Profiles= 1
Profile Names=01pct
River Rch & RM=MILLSITERN,Main,12527
     441
River Rch & RM=MILLSITERN,Main,9877
     499
River Rch & RM=MILLSITERN,Main,5932
     558
River Rch & RM=MILLSITERN,Main,4700
     620
Boundary for River Rch & Prof#=MILLSITERN,Main            , 1
Up Type= 0
Dn Type= 3
Dn Slope=0.00844
DSS Import GetInterval= 0
DSS Import GetPeak= 0
DSS Import FillOption= 0

--- MILLSITERN.g01 (geometry) ---

Geom Title=Geometry
Program Version=6.31

River Reach=MILLSITERN      ,Main
Reach XY= 30
2194736.00900003641016.8400000042194568.08800004640941.493000016
2193860.20400003641104.4350000022193307.47900005640885.519999996
2192998.45000002 640984.990000012192614.87600003      640857.103
     2192397.191641056.702999994     2192204.947641068.464000002
     2192036.596      640597.0662191788.00599998640573.315000013
2191818.19600001 640313.363000022191555.09700003 640207.82600002
2191190.83899999639819.930999994     2190730.745639680.769999996
2190706.62100004639566.5900000182190314.97700003639541.122000009
2190353.92399998639283.344999999     2190130.287639330.648000017
2190043.06399998639080.5690000062189682.72700003638913.307000011
2189619.36999999638770.683000013     2189204.175638801.388000011
2188266.24400003639273.5010000022187445.52600002639444.856000021
2187130.60300002639862.3690000032186726.42499998 639910.76000002
2186870.13600004 640055.902000012187010.52800001640531.506000012
2187280.03800003      640667.9782187617.19587067641240.677553922

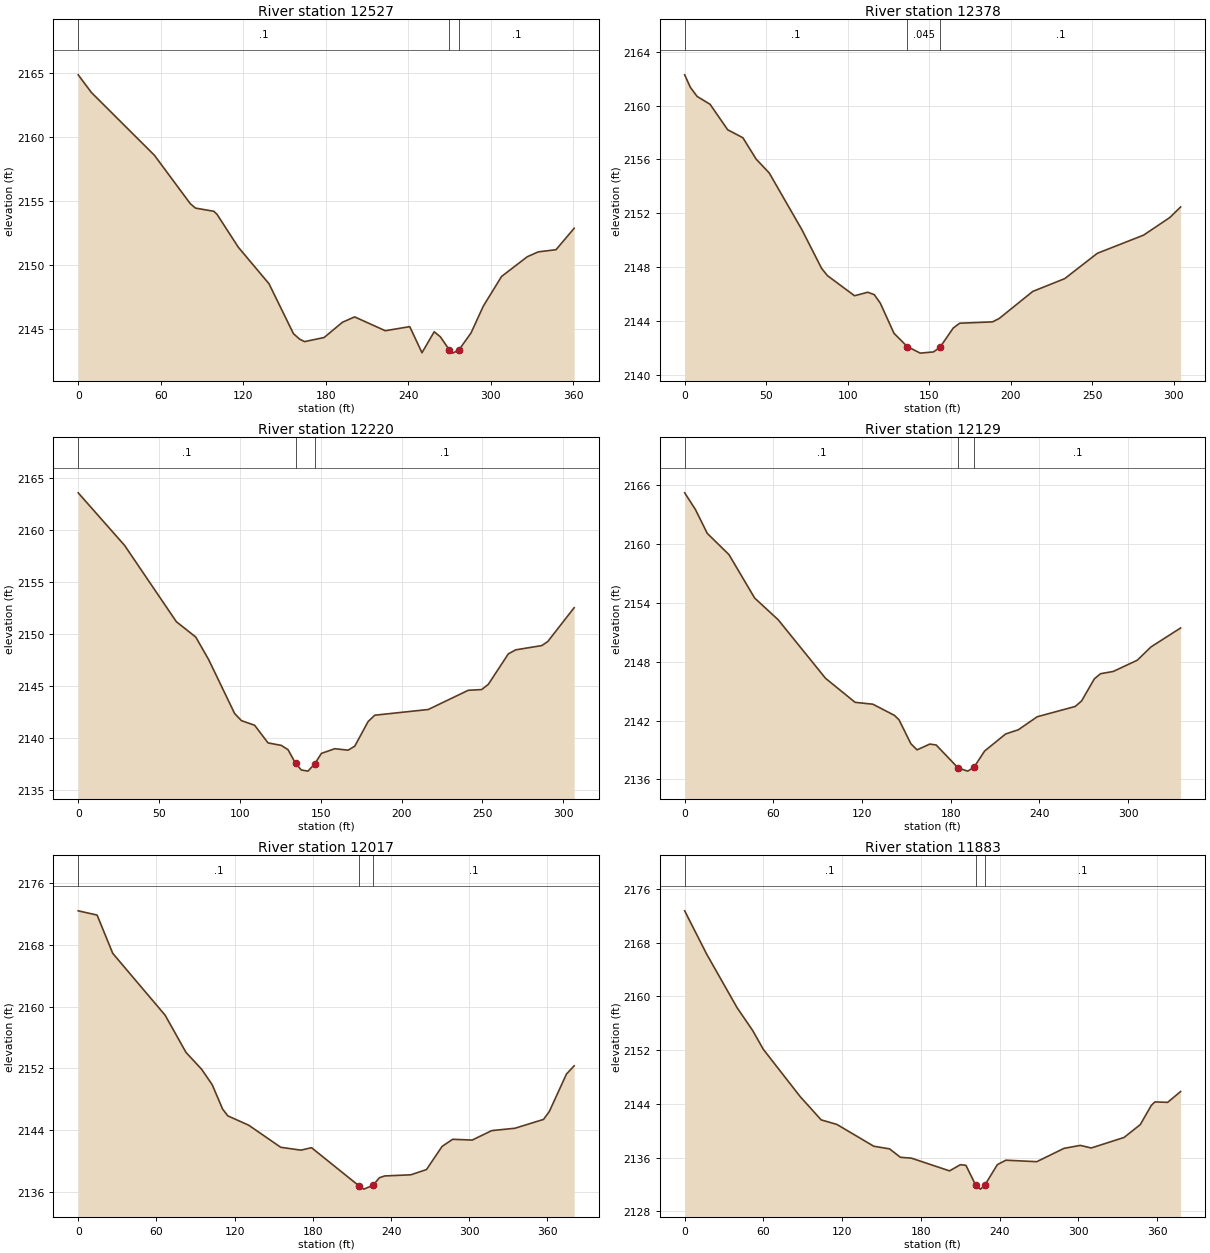
Type RM Length L Ch R = 1 ,12527   ,148.9,148.9,148.9
XS GIS Cut Line= 2
 2194844.5906281 640768.530971842194685.91521576641092.614924219
#Sta/Elev= 30
       0 2164.85     9.6 2163.47    55.5 2158.56    81.5 2154.79    85.3 2154.44
    98.7 2154.19     101 2153.95   116.5 2151.38   138.8 2148.53   156.6 2144.63
   161.1  2144.2   164.7 2144.01   178.9 2144.33   192.2 2145.52   201.1 2145.94
   223.4 2144.86   241.2 2145.18   250.1 2143.14     259 2144.78   263.5 2144.38
   269.9 2143.38   272.4 2143.11   276.9 2143.35   285.8 2144.69   294.7 2146.78
     308  2149.1   326.7 2150.64   334.7 2151.02   347.6 2151.19   360.8 2152.86
#Mann= 3 ,-1,0
       0      .1       0   269.9    .045       0   276.9      .1       0
Bank Sta=269.9,276.9
XS Rating Curve= 0 ,0
Exp/Cntr(USF)=0,0
Exp/Cntr=0.3,0.1

Type RM Length L Ch R = 1 ,12378   ,159.4,158.1,156.2
XS GIS Cut Line= 2
2194582.37079846640797.6812244132194618.34785718641099.699164769
#Sta/Elev= 30
       0 2162.28     3.5 2161.35     7.6 2160.68    15.6 2160.09    26.4  2158.2
    35.7 2157.61    43.8 2156.03    51.9 2154.99      72 2150.76      84 2147.91
    87.6 2147.37   104.2 2145.88   112.3 2146.14   116.3 2145.96     120 2145.33
   128.4 2143.09   136.5 2142.11   144.5 2141.62   152.6 2141.71   156.6 2142.05
   164.7 2143.48   168.7 2143.84   188.8 2143.94   192.9 2144.19   213.5  2146.2
   233.1 2147.15   253.1 2149.03   281.5 2150.38   297.6 2151.69   304.2 2152.47
#Mann= 3 ,-1,0
       0      .1       0   136.5    .045       0   156.6      .1       0
Bank Sta=136.5,156.6
XS Rating Curve= 0 ,0
Exp/Cntr(USF)=0,0
Exp/Cntr=0.3,0.1

Type RM Length L Ch R = 1 ,12220   ,91.4,90.5,88.4
XS GIS Cut Line= 3
2194439.40932825640836.4985772492194436.56903415640933.068576986
2194488.64109283641136.622988198
#Sta/Elev= 30
       0  2163.6    28.7 2158.53    60.7 2151.18    72.7  2149.7    80.7 2147.52
    96.7 2142.34   100.9 2141.65   109.1  2141.2   117.4  2139.5   125.6 2139.26
   129.8 2138.84   134.42137.531     138 2136.89   142.1 2136.78   146.3 2137.49
   150.4 2138.49   158.7 2138.94   166.9  2138.8     171 2139.18   179.3 2141.56
   183.4 2142.17   216.5 2142.72   241.2 2144.57   249.5 2144.64   253.6 2145.14
     266 2148.08   270.6 2148.47   286.7 2148.88   290.4 2149.27   306.7 2152.53
#Mann= 3 ,-1,0
       0      .1       0   134.4    .045       0   146.3      .1       0
Bank Sta=134.4,146.3
XS Rating Curve= 0 ,0
Exp/Cntr(USF)=0,0
Exp/Cntr=0.3,0.1

Type RM Length L Ch R = 1 ,12129   ,107.7,111.7,117
XS GIS Cut Line= 3
2194349.46668144640829.8712243262194349.46668144640957.684459272
 2194423.3143283641151.771223451
#Sta/Elev= 30
       0 2165.24     7.3 2163.53    15.3  2161.1      30 2158.93    47.3 2154.51
    63.3 2152.28    95.3 2146.31   115.3 2143.86   127.3 2143.67   141.9 2142.53
     145 2142.08     153 2139.64   157.2 2139.01   165.8  2139.6   170.1 2139.51
     1852137.165   191.5 2136.84   195.7 2137.23   202.9 2138.89   217.1 2140.63
   225.7 2141.06   238.5 2142.39   264.2 2143.44   268.5    2144   277.1 2146.25
   281.3 2146.78   289.9 2147.01   306.2 2148.16   315.5 2149.52   335.5 2151.45
#Mann= 3 ,-1,0
       0      .1       0     185    .045       0   195.7      .1       0
Bank Sta=185,195.7
XS Rating Curve= 0 ,0
Exp/Cntr(USF)=0,0
Exp/Cntr=0.3,0.1

Type RM Length L Ch R = 1 ,12017   ,137.2,134.4,130.3
XS GIS Cut Line= 3
2194276.20564393640798.7102986972194254.41878241641091.842617389
2194290.52803589641170.537945068
#Sta/Elev= 30
       0 2172.44    14.5 2171.89    26.5 2166.92    66.7 2158.89    82.7 2154.06
    94.7 2151.87   102.8 2149.87   110.8  2146.7   114.8 2145.82   130.8 2144.61
   155.4 2141.74   170.9 2141.37     179 2141.69   215.1 2136.78   215.1 2136.77
   219.1 2136.31   226.12136.793   231.1 2137.79   235.1 2138.02   255.2 2138.17
   267.2 2138.85   279.2 2141.86   287.3 2142.78   302.3 2142.68   317.3 2143.91
     335 2144.21     357 2145.36   361.4 2146.37   374.6 2151.25   380.5 2152.32
#Mann= 3 ,-1,0
       0      .1       0   215.1    .045       0   226.1      .1       0
Bank Sta=215.1,226.1
XS Rating Curve= 0 ,0
Exp/Cntr(USF)=0,0
Exp/Cntr=0.3,0.1

Type RM Length L Ch R = 1 ,11883   ,188.1,189,189.3
XS GIS Cut Line= 3
2194120.34962324640821.3503419962194110.88197621640977.566518042
2194170.75746681641190.740209732
#Sta/Elev= 30
       0 2172.76    16.7 2166.33    39.9 2158.34    51.9  2154.9    59.9 2152.13
      88 2145.08     104 2141.61     116 2140.93   144.1 2137.68   156.1 2137.29
   164.4 2136.03   172.7 2135.91   201.8 2134.01   210.1 2134.93   214.3 2134.84
   221.82131.871   225.4 2131.29   228.6 2131.86   238.3 2134.95   244.8  2135.6
   268.3 2135.38   289.1 2137.37   301.5 2137.81   309.8 2137.42   334.8 2138.99
   347.2 2140.91   355.5 2143.75   358.3 2144.29     368 2144.22   377.9 2145.83
#Mann= 3 ,-1,0
       0      .1       0   221.8    .045       0   228.6      .1       0
Bank Sta=221.8,228.6
XS Rating Curve= 0 ,0
Exp/Cntr(USF)=0,0
Exp/Cntr=0.3,0.1

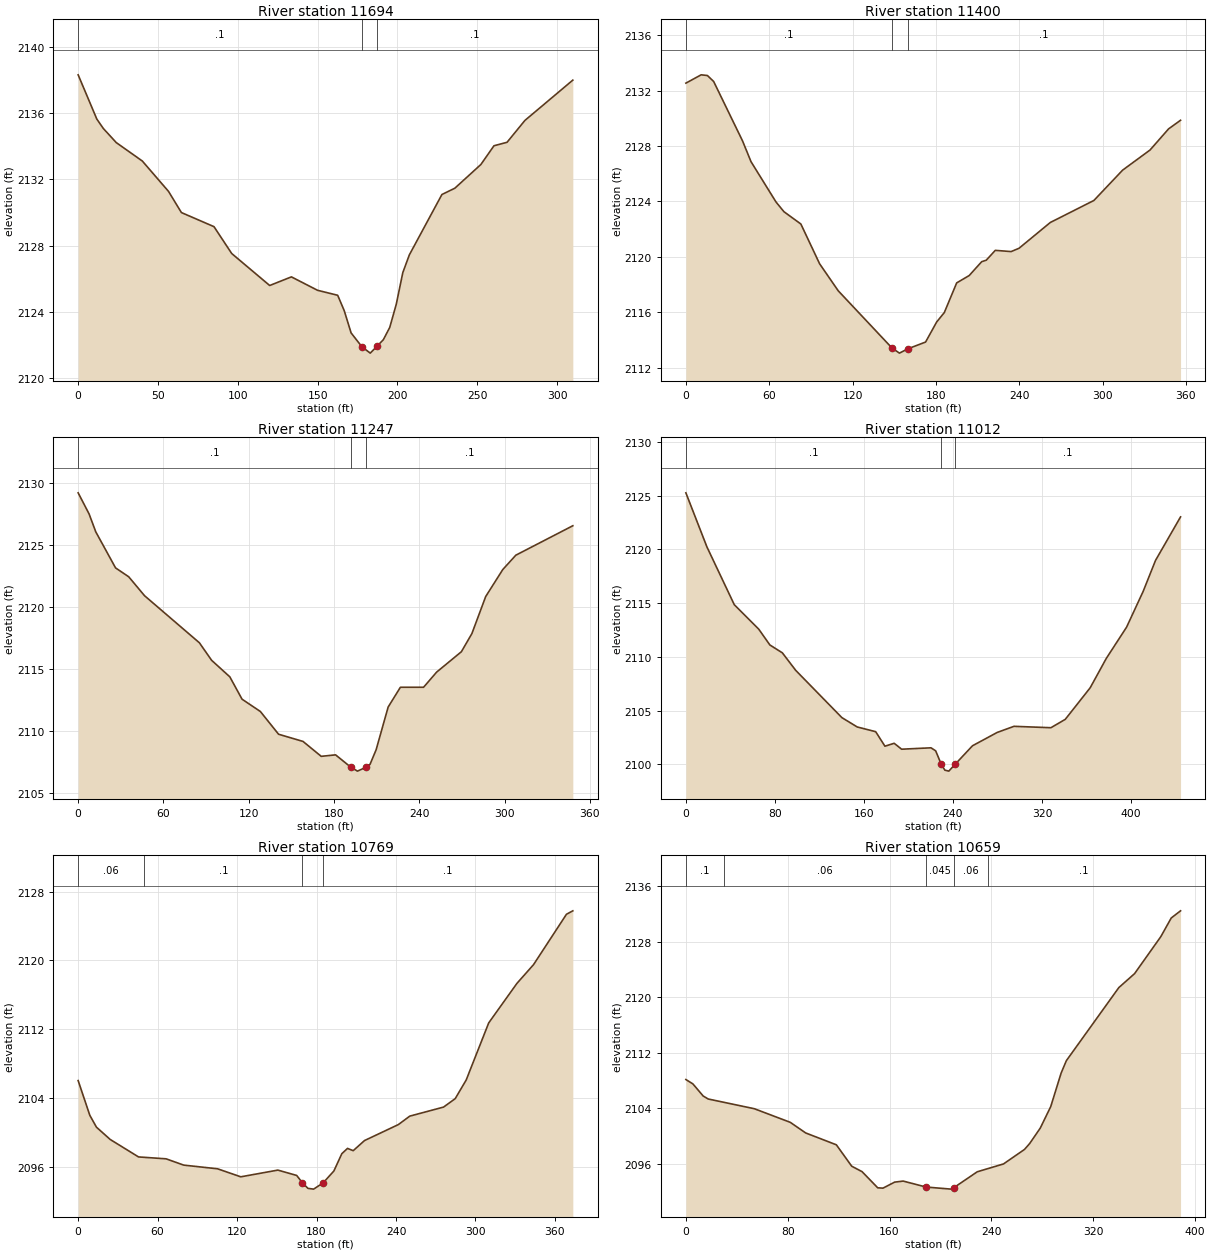
Type RM Length L Ch R = 1 ,11694   ,286.3,293.8,300.4
XS GIS Cut Line= 2
2193922.47580025640921.7074005472193983.06874126641225.618870309
#Sta/Elev= 30
       0  2138.3    11.7 2135.63    15.8 2135.06    23.9 2134.21    40.2  2133.1
    56.6 2131.27    64.7 2129.99    85.1 2129.14    96.2 2127.52     120 2125.59
   133.6 2126.11     150  2125.3   162.6    2125   166.7 2124.07     171 2122.73
   177.8 2121.89     183 2121.51   187.1 2121.91   191.2 2122.32   195.2 2123.06
   199.3 2124.46   203.4 2126.37   207.5 2127.44   227.9 2131.08     236 2131.46
   252.3 2132.89   260.5 2134.02   268.7 2134.23   279.9 2135.55   309.9 2137.98
#Mann= 3 ,-1,0
       0      .1       0   177.8    .045       0   187.1      .1       0
Bank Sta=177.8,187.1
XS Rating Curve= 0 ,0
Exp/Cntr(USF)=0,0
Exp/Cntr=0.3,0.1

Type RM Length L Ch R = 1 ,11400   ,153.7,153,152
XS GIS Cut Line= 2
2193765.26915462640883.377183051 2193603.6510373641200.841342064
#Sta/Elev= 30
       0 2132.54      11 2133.14    15.5 2133.09      20 2132.66    40.8 2128.37
    46.9 2126.87    64.9 2123.96    70.6 2123.26    82.8 2122.37    96.3  2119.5
   109.7 2117.55   148.52113.411   153.8 2113.05   159.8 2113.36   172.6 2113.85
   180.6  2115.3   186.1 2115.98     195 2118.12     204 2118.65     213 2119.65
   216.3 2119.76   222.8 2120.47   234.2 2120.38   239.9 2120.62   262.4 2122.48
   293.8 2124.07   314.5 2126.26   334.2 2127.71   347.6 2129.24   356.2 2129.86
#Mann= 3 ,-1,0
       0      .1       0   148.5    .045       0   159.8      .1       0
Bank Sta=148.5,159.8
XS Rating Curve= 0 ,0
Exp/Cntr(USF)=0,0
Exp/Cntr=0.3,0.1

Type RM Length L Ch R = 1 ,11247   ,236.2,235.4,233.4
XS GIS Cut Line= 2
2193618.56433049640817.5632831832193493.59138965641142.303576418
#Sta/Elev= 30
       0 2129.19     7.7 2127.49    12.4 2126.05    26.3 2123.15    35.6 2122.43
    46.7 2120.91    85.3 2117.12    93.9 2115.71   106.7 2114.38   115.3 2112.58
   128.2 2111.59     141 2109.76   158.2 2109.18     171 2107.98   181.1  2108.1
  191.872107.103   196.5 2106.79   202.7 2107.11   205.3 2107.33   209.6  2108.5
   218.1 2111.95   226.7 2113.54     243 2113.54   252.2 2114.76   269.6  2116.4
     277 2117.86   286.7 2120.84   298.7 2123.01   307.9 2124.17     348 2126.54
#Mann= 3 ,-1,0
       0      .1       0  191.87    .045       0   202.7      .1       0
Bank Sta=191.87,202.7
XS Rating Curve= 0 ,0
Exp/Cntr(USF)=0,0
Exp/Cntr=0.3,0.1

Type RM Length L Ch R = 1 ,11012   ,249,243.2,234.5
XS GIS Cut Line= 3
2193498.32521317640745.609165731 2193365.7781547640818.510047886
2193289.09021373641101.592694176
#Sta/Elev= 30
       0 2125.27    18.9 2120.24    43.5 2114.86    65.5 2112.58    75.5 2111.11
    86.7 2110.38    98.7 2108.75   140.2 2104.35     154 2103.48   170.6 2103.04
   178.9 2101.69   187.2 2101.96   193.9 2101.41   220.3 2101.54   224.5 2101.26
   229.62099.988   232.8 2099.46   236.3 2099.37   242.12100.015   257.6 2101.73
   279.8 2102.97   294.9 2103.54   328.1 2103.41     341 2104.19   363.4 2107.13
   377.8 2109.85   396.1 2112.77     411  2116.1   422.1 2118.98   444.6 2123.03
#Mann= 3 ,-1,0
       0      .1       0   229.6    .045       0   242.1      .1       0
Bank Sta=229.6,242.1
XS Rating Curve= 0 ,0
Exp/Cntr(USF)=0,0
Exp/Cntr=0.3,0.1

Type RM Length L Ch R = 1 ,10769   ,107.3,109.1,109.5
XS GIS Cut Line= 2
2193057.13286142640766.4379892042193186.83962578641116.740929428
#Sta/Elev= 30
       0 2106.04     8.8 2102.01    13.8 2100.63    24.2  2099.2    45.6 2097.17
    66.4 2096.95    79.7 2096.22   105.3 2095.79   122.8 2094.86   150.8 2095.64
     165 2095.02   169.3 2094.17   173.5 2093.52   177.8 2093.43     185 2094.16
   193.1 2095.54   199.1 2097.55   203.4 2098.16   207.7  2097.9   216.2 2099.07
   241.8 2100.93   250.4 2101.91   275.9 2102.96   284.7 2103.94     293 2106.11
     310 2112.74   331.3 2117.33   343.8  2119.5   368.7 2125.36   373.5 2125.76
#Mann= 4 ,-1,0
       0     .06       0      50      .1       0   169.3    .045       0
     185      .1       0
Bank Sta=169.3,185
XS Rating Curve= 0 ,0
Exp/Cntr(USF)=0,0
Exp/Cntr=0.3,0.1

Type RM Length L Ch R = 1 ,10659   ,57.5,83.8,94
XS GIS Cut Line= 3
2193023.99609681 640779.692695052193008.84786155640916.026812327
2193068.49403786641160.292105781
#Sta/Elev= 30
       0 2108.11     5.5 2107.48    13.6 2105.73    17.6  2105.3    53.8  2103.9
      82 2101.94    94.1 2100.41   118.2  2098.7   130.3 2095.61   138.4 2094.83
   150.7  2092.5   154.8 2092.45     164 2093.32   170.7 2093.47   188.7 2092.61
   208.4 2092.31   210.5 2092.52   228.9 2094.81   249.5 2095.94     266 2098.03
   270.1 2098.89   278.4 2101.11   286.6  2104.2   294.8 2109.05   298.9 2110.83
   340.1 2121.36   352.5 2123.38   373.1 2128.71   381.3  2131.4   388.6 2132.43
#Mann= 5 ,-1,0
       0      .1       0      30     .06       0   188.7    .045       0
   210.5     .06       0  237.17      .1       0
Bank Sta=188.7,210.5
XS Rating Curve= 0 ,0
Exp/Cntr(USF)=0,0
Exp/Cntr=0.3,0.1

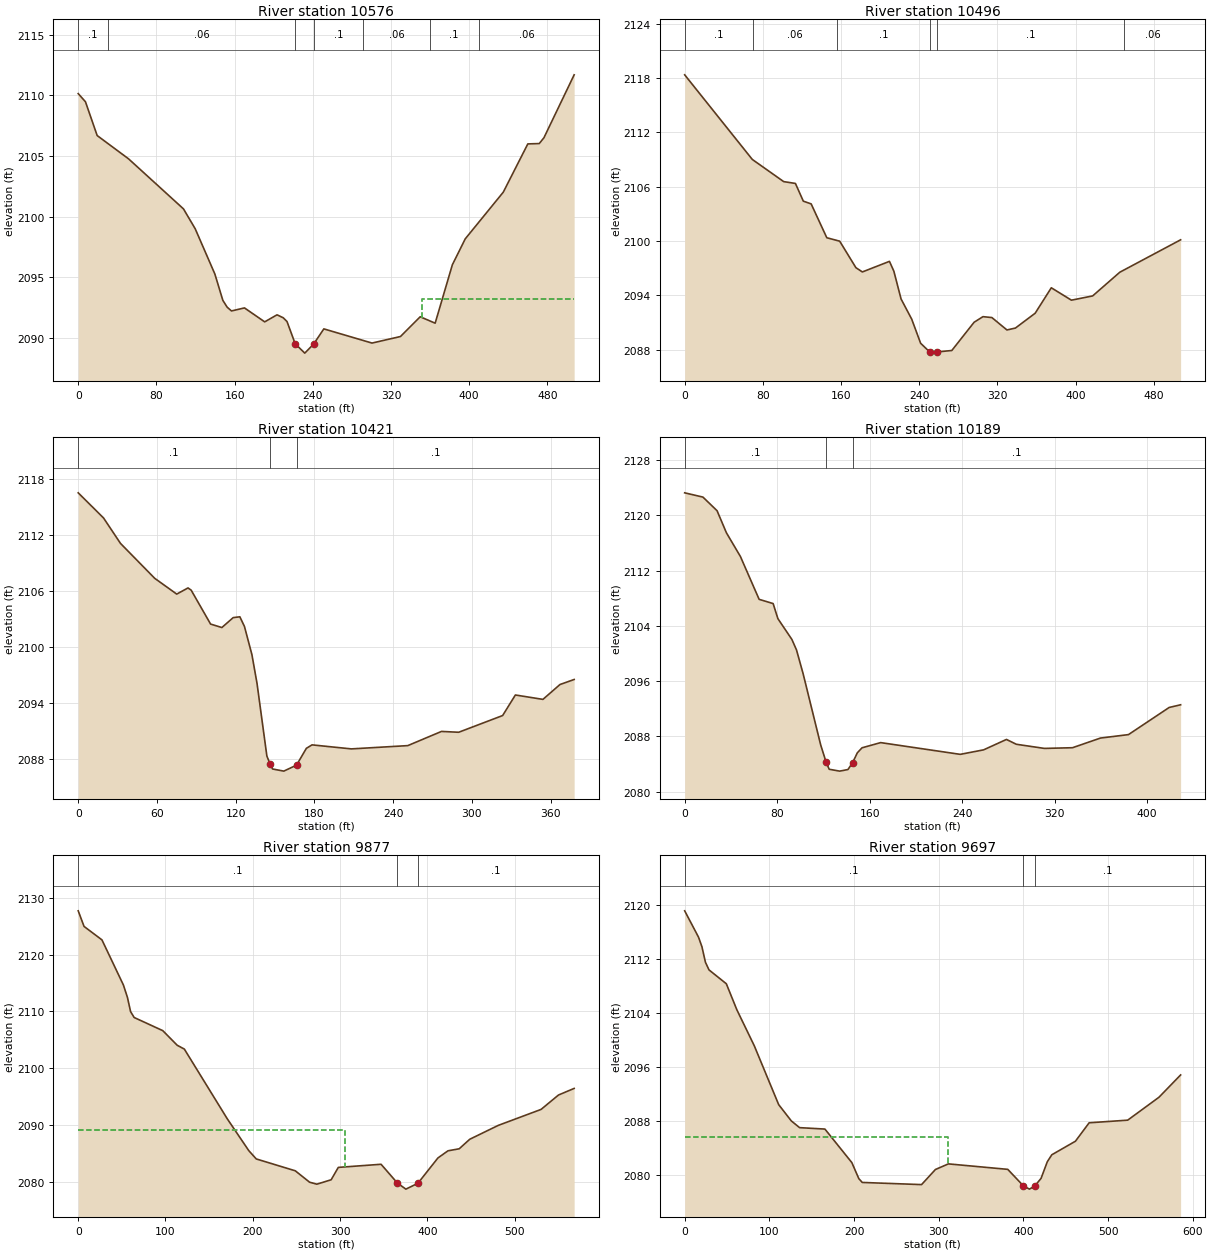
Type RM Length L Ch R = 1 ,10576   ,89.9,79.8,77.4
XS GIS Cut Line= 5
2193014.52844977640777.7991656442193003.16727333640923.600929954
2192988.01903808640955.7909298662192858.31227373641026.798282614
2192814.76109738641199.109458617
#Sta/Elev= 30
       0 2110.15     7.4 2109.48    19.4 2106.69    51.5 2104.77   107.7 2100.64
   119.7    2099   139.8 2095.27     148 2093.09   152.4 2092.53   156.8 2092.22
   170.1 2092.47   190.8 2091.32   203.4  2091.9   209.7 2091.66   213.6 2091.35
  222.02 2089.51   231.8 2088.74   240.9 2089.49   251.3 2090.74   300.6 2089.57
   329.7 2090.11   349.9 2091.74   365.2 2091.21   382.8 2096.03     396 2098.17
   434.9 2102.02     460    2106   471.7 2106.03   476.5 2106.51   507.4  2111.7
#Mann= 7 ,-1,0
       0      .1       0      30     .06       0  222.02    .045       0
   240.9      .1       0  291.82     .06       0  359.69      .1       0
  409.69     .06       0
#XS Ineff= 2 , 0
                          352.23         2093.19
Permanent Ineff=
       F       F
Bank Sta=222.02,240.9
XS Rating Curve= 0 ,0
Exp/Cntr(USF)=0,0
Exp/Cntr=0.3,0.1

Type RM Length L Ch R = 1 ,10496   ,82.7,74.6,69.7
XS GIS Cut Line= 5
2192962.92977344640744.189018676  2192951.568597640889.990782986
2192936.42036175640922.180782898 2192806.7135974640993.188135647
2192763.16242105641165.499311649
#Sta/Elev= 30
       0 2118.35    69.2    2109   101.3 2106.55   113.3 2106.35   121.4 2104.39
   129.4 2104.09   145.4 2100.35   158.6 2099.97   175.2 2097.04   181.8 2096.57
   209.5 2097.74     214 2096.66   221.4 2093.58   232.3 2091.35   241.4 2088.69
   250.5 2087.75   254.7  2087.6   257.82087.726   273.3 2087.89   296.1 2091.01
   305.2 2091.63   314.3 2091.53   329.7 2090.16   338.4 2090.37   358.6 2092.01
   375.1 2094.82   395.7 2093.45   417.4 2093.92   445.2 2096.54   507.4 2100.12
#Mann= 6 ,-1,0
       0      .1       0      70     .06       0  156.24      .1       0
   250.5    .045       0   257.8      .1       0  449.69     .06       0
Bank Sta=250.5,257.8
XS Rating Curve= 0 ,0
Exp/Cntr(USF)=0,0
Exp/Cntr=0.3,0.1

Type RM Length L Ch R = 1 ,10421   ,239.1,232.7,227.2
XS GIS Cut Line= 2
2192869.67345017640771.1718127212192732.39256819641123.368282352
#Sta/Elev= 30
       0 2116.53    19.3 2113.84    32.2 2111.12    58.3 2107.38    75.1 2105.69
    83.7 2106.35    86.1 2106.11   100.9 2102.48   109.5 2102.11   118.1 2103.17
   123.2 2103.26   126.7 2102.23   132.4 2099.21   136.3 2096.12   143.8 2088.35
   146.3 2087.49   148.1 2086.97   156.7 2086.74   166.4 2087.38   173.9 2089.18
   178.2 2089.55   208.2 2089.12   251.2 2089.47   276.9 2090.99     290  2090.9
   323.5 2092.69   333.2 2094.89   354.2 2094.42   367.2 2096.01     378 2096.55
#Mann= 3 ,-1,0
       0      .1       0   146.3    .045       0   166.4      .1       0
Bank Sta=146.3,166.4
XS Rating Curve= 0 ,0
Exp/Cntr(USF)=0,0
Exp/Cntr=0.3,0.1

Type RM Length L Ch R = 1 ,10189   ,308.4,311.4,315.5
XS GIS Cut Line= 2
2192571.44256863640729.5141657752192634.87580375641153.664752858
#Sta/Elev= 30
       0 2123.27    15.8 2122.65      28 2120.68    36.1 2117.48    48.2 2114.05
    64.4 2107.84    76.5 2107.23    80.6 2105.05    92.7 2102.04    96.7 2100.52
   102.4 2097.09   117.6 2086.77   122.4 2084.21     125 2083.23     134 2082.96
   141.2 2083.19   145.3  2084.2   149.3 2085.61   153.4 2086.34   169.5 2087.09
   238.3 2085.39   258.5 2086.04   278.3 2087.55   286.8 2086.85   311.1 2086.25
   335.4 2086.35   359.6 2087.75   383.8 2088.25     419 2092.18   428.9 2092.57
#Mann= 3 ,-1,0
       0      .1       0   122.4    .045       0   145.3      .1       0
Bank Sta=122.4,145.3
XS Rating Curve= 0 ,0
Exp/Cntr(USF)=0,0
Exp/Cntr=0.3,0.1

Type RM Length L Ch R = 1 ,9877    ,164.6,180,195.9
XS GIS Cut Line= 3
2192445.14072292640690.655621805 2192372.0322377641011.539772875
2192414.51118148641246.836872643
#Sta/Elev= 30
       0 2127.74     6.7 2124.99    27.2 2122.62    51.8 2114.66    56.4 2112.48
      60 2109.98    64.1 2108.94    96.9 2106.62   113.4 2104.05   121.6 2103.37
   170.8 2091.08   195.4 2085.48     204 2084.01   248.7 2081.92   265.1 2079.91
   273.4 2079.56   289.8 2080.34     298 2082.52     347 2083.07   365.7 2079.76
   375.4 2078.69   389.2 2079.72   412.1 2084.18   423.6 2085.44   436.5  2085.8
   448.6 2087.48   481.2 2089.92   530.3 2092.74   550.3 2095.28   568.2 2096.44
#Mann= 3 ,0,0
       0      .1       0   365.7    .045       0   389.2      .1       0
#XS Ineff= 2 , 0
          305.39 2089.15
Permanent Ineff=
       F       F
Bank Sta=365.7,389.2
XS Rating Curve= 0 ,0
Exp/Cntr(USF)=0,0
Exp/Cntr=0.3,0.1

Type RM Length L Ch R = 1 ,9697    ,184.9,190.8,196.2
XS GIS Cut Line= 3
2192344.21903983640697.3241658622192268.47786357641010.703282658
2192068.71051117641182.067693957
#Sta/Elev= 30
       0 2119.11    16.3 2115.22    20.4 2113.78    24.5 2111.49    28.7 2110.36
    49.2  2108.3    61.6 2104.45    82.2 2099.11     111 2090.39   125.9 2087.98
   135.7 2086.98   165.6 2086.77   197.4  2081.8   205.6 2079.43   209.7 2078.86
   279.7 2078.54   296.1 2080.78   311.4 2081.61   381.5  2080.8   399.9 2078.36
   407.1 2077.87   413.5 2078.35   420.8 2079.46   428.2 2081.93   433.5 2082.96
   461.4 2084.97   477.6  2087.7   523.1 2088.09     560 2091.48   585.6 2094.79
#Mann= 3 ,-1,0
       0      .1       0   399.9    .045       0   413.5      .1       0
#XS Ineff= 2 , 0
          310.99 2085.56
Permanent Ineff=
       F       F
Bank Sta=399.9,413.5
XS Rating Curve= 0 ,0
Exp/Cntr(USF)=0,0
Exp/Cntr=0.3,0.1

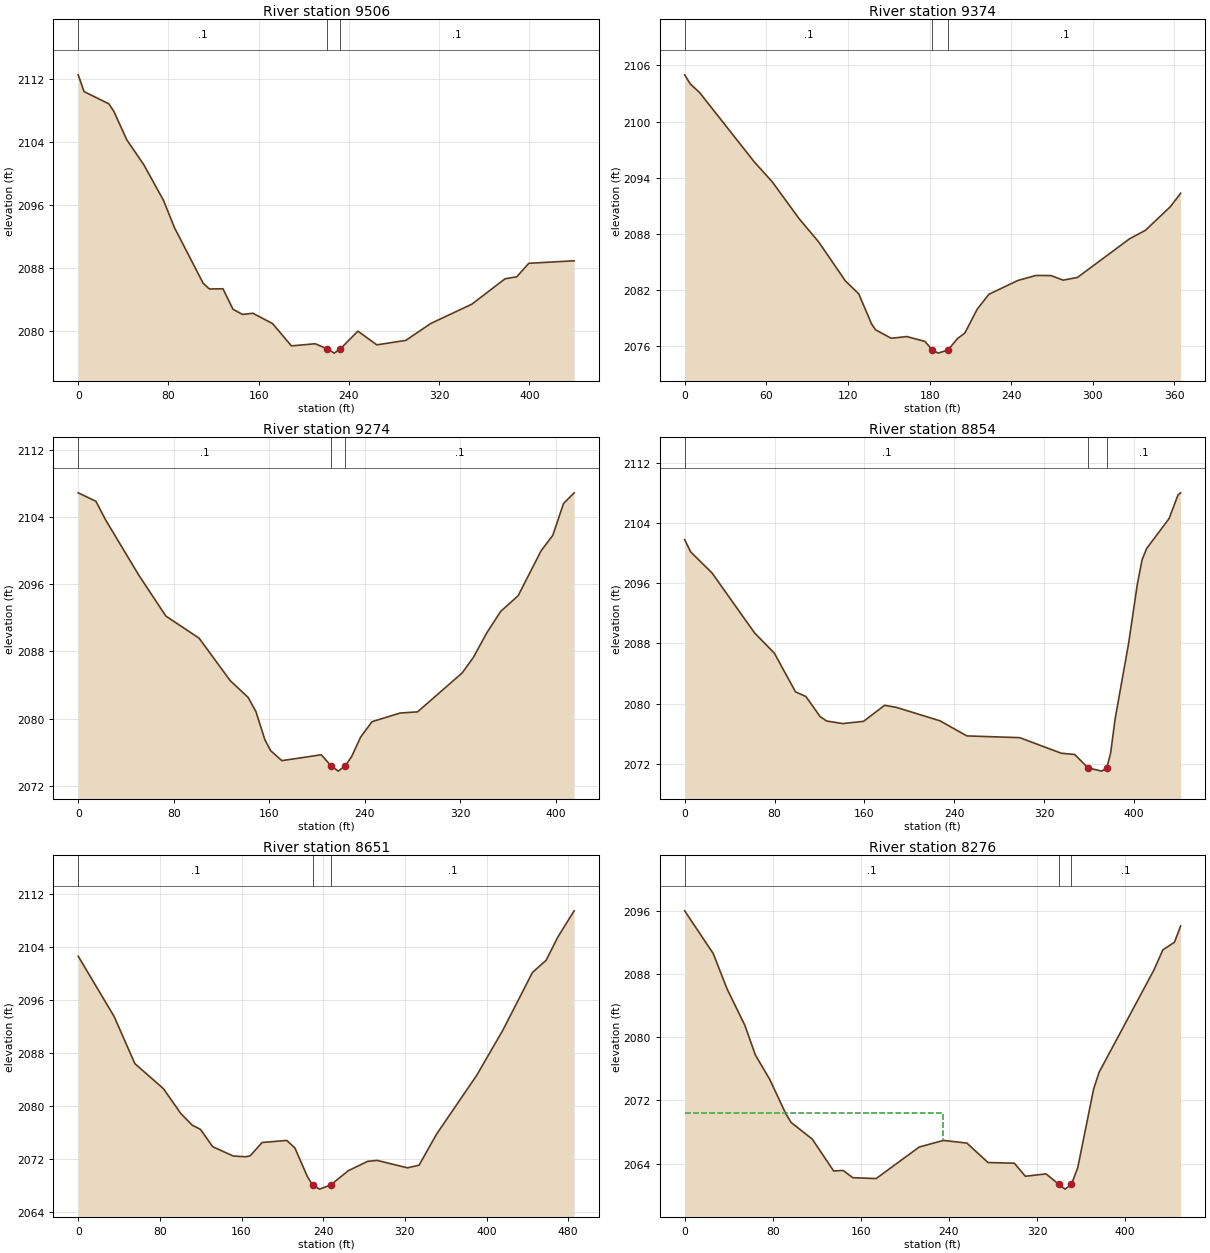
Type RM Length L Ch R = 1 ,9506    ,134.3,132,126.6
XS GIS Cut Line= 3
2192320.54992225640712.472401115 2192249.5425695640867.741812458
2191993.91609961640951.057106349
#Sta/Elev= 30
       0 2112.48     5.2 2110.35    27.2  2108.8    31.6 2107.84    43.1 2104.22
    58.2 2101.06    75.6 2096.55    85.3 2093.09   110.7 2086.04   116.3  2085.3
   128.3 2085.33   137.1 2082.75   139.7 2082.53   145.7 2082.07   154.8 2082.22
   172.2 2080.92     189 2078.08     210 2078.35   220.72077.708   226.9 2077.16
  232.262077.688   247.9 2079.95   264.7 2078.21   290.4 2078.78   312.6 2080.93
   348.9 2083.37   378.3 2086.59   388.7 2086.85   399.4 2088.56   439.6 2088.88
#Mann= 3 ,-1,0
       0      .1       0   220.7    .045       0  232.26      .1       0
Bank Sta=220.7,232.26
XS Rating Curve= 0 ,0
Exp/Cntr(USF)=0,0
Exp/Cntr=0.3,0.1

Type RM Length L Ch R = 1 ,9374    ,99.7,100.5,100.7
XS GIS Cut Line= 2
2192257.11668713640706.7918128952191957.93904088640915.080047623
#Sta/Elev= 30
       0 2104.99     4.2    2104      11 2103.09    51.2 2095.68    64.5 2093.53
      84 2089.64    98.6 2087.11   118.1 2082.97   127.9 2081.59   137.4 2078.36
   140.3 2077.74   151.8 2076.84   163.3 2077.02   176.6  2076.5   181.92075.604
   186.3 2075.25  193.452075.581   200.7 2076.83   205.9 2077.39     215 2079.95
   223.6 2081.54   244.8 2083.01   258.1 2083.55   269.2 2083.54   278.2 2083.05
   288.7 2083.34   327.1 2087.48   338.6 2088.37   356.9 2090.89   364.5 2092.33
#Mann= 3 ,-1,0
       0      .1       0   181.9    .045       0  193.45      .1       0
Bank Sta=181.9,193.45
XS Rating Curve= 0 ,0
Exp/Cntr(USF)=0,0
Exp/Cntr=0.3,0.1

Type RM Length L Ch R = 1 ,9274    ,410.8,420,426.1
XS GIS Cut Line= 2
2192228.74797657640618.2998986812191876.63708324640838.369207008
#Sta/Elev= 30
       0 2106.89    14.8 2105.89    22.8  2103.7    50.7 2097.09    73.4 2092.21
   101.2 2089.58   127.3 2084.51   142.2 2082.53   148.8 2080.83   156.3 2077.47
   161.1 2076.18   170.5 2074.99   203.5 2075.69   211.5  2074.4   217.7 2073.74
  223.622074.374   228.9 2075.47   236.5 2077.81     246 2079.63   269.5 2080.66
   284.1  2080.8   321.4 2085.43   330.9  2087.3   342.1 2090.22   353.7 2092.77
   368.3 2094.63   387.5 2099.98   397.3 2101.82   406.3 2105.62   415.2 2106.89
#Mann= 3 ,-1,0
       0      .1       0   211.5    .045       0  223.62      .1       0
Bank Sta=211.5,223.62
XS Rating Curve= 0 ,0
Exp/Cntr(USF)=0,0
Exp/Cntr=0.3,0.1

Type RM Length L Ch R = 1 ,8854    ,203.9,203.5,200
XS GIS Cut Line= 3
2192120.78256985640448.325048892 2191936.1634527640559.096519179
2191709.88668861640561.936813289
#Sta/Elev= 30
       0 2101.79     5.4 2100.16    24.4 2097.36    62.3 2089.39    79.8 2086.72
    98.7 2081.57     108 2080.94   120.6 2078.28   126.4 2077.69   140.7 2077.35
   159.3 2077.65     178 2079.78   188.3 2079.51   227.3 2077.72   251.3 2075.71
   298.3 2075.48   335.3 2073.41   347.3 2073.24   359.2 2071.46   371.3 2071.03
  375.862071.465   379.3 2073.45   383.3 2077.99   395.3 2088.02     403 2095.82
   407.3 2099.13   411.3 2100.61   431.3 2104.59   439.3 2107.75   441.6 2108.02
#Mann= 3 ,-1,0
       0      .1       0   359.2    .045       0  375.86      .1       0
Bank Sta=359.2,375.86
XS Rating Curve= 0 ,0
Exp/Cntr(USF)=0,0
Exp/Cntr=0.3,0.1

Type RM Length L Ch R = 1 ,8651    ,383.1,374.6,358.1
XS GIS Cut Line= 3
2192091.17825055 640362.918269142191760.69136746640399.817290067
2191656.41152571640512.118658106
#Sta/Elev= 30
       0 2102.55    35.2 2093.46    55.5 2086.36    83.5 2082.58   100.5 2078.84
   111.7 2077.08   119.7 2076.45   131.8 2073.83   151.9 2072.43     164 2072.32
   168.5 2072.47   180.1 2074.47   204.3 2074.78   212.3 2073.64   224.4 2069.36
  229.512068.061   236.4 2067.44   247.3 2068.07   264.6 2070.22   283.6 2071.63
   292.8 2071.77   322.5 2070.65   333.9 2071.05   350.9  2075.7   390.5 2084.63
     416 2091.41     445 2100.11   458.4 2101.94   469.7 2105.41   485.8 2109.39
#Mann= 3 ,-1,0
       0      .1       0  229.51    .045       0   247.3      .1       0
Bank Sta=229.51,247.3
XS Rating Curve= 0 ,0
Exp/Cntr(USF)=0,0
Exp/Cntr=0.3,0.1

Type RM Length L Ch R = 1 ,8276    ,237.9,237,234.1
XS GIS Cut Line= 2
2191756.23496397639925.2994460662191503.11124553640297.854778133
#Sta/Elev= 30
       0    2096    25.9  2090.6    38.5 2086.12    54.7 2081.49    64.2 2077.75
    77.2 2074.67    91.7 2070.35    96.6 2069.21   115.9 2067.09   135.3 2063.06
   143.9 2063.13   152.6 2062.21   173.9  2062.1     213 2066.09     235 2066.93
   256.3 2066.59   275.5 2064.13   299.4 2064.04   309.4 2062.39   328.2 2062.69
   339.7 2061.38   345.5 2060.76   351.3 2061.38     357 2063.49   371.4 2073.44
   376.4 2075.57   426.1 2088.49   434.3 2091.06   444.8 2092.02   450.4 2094.08
#Mann= 3 ,-1,0
       0      .1       0   339.7    .045       0   351.3      .1       0
#XS Ineff= 2 , 0
          234.93 2070.44
Permanent Ineff=
       T       F
Bank Sta=339.7,351.3
XS Rating Curve= 0 ,0
Exp/Cntr(USF)=0,0
Exp/Cntr=0.3,0.1

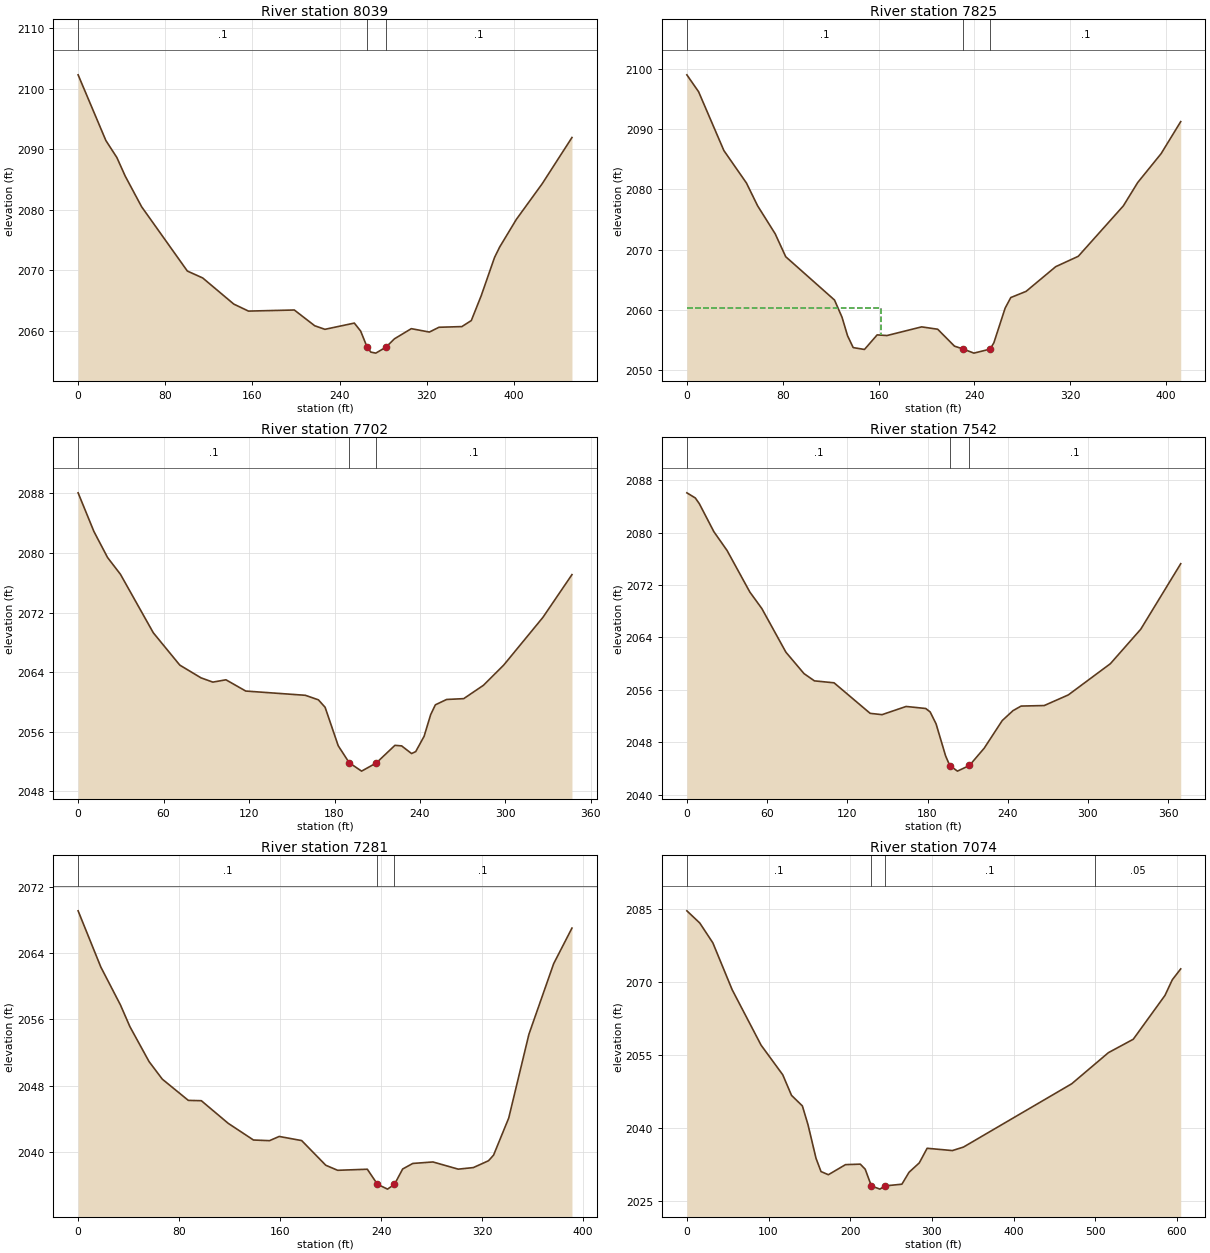
Type RM Length L Ch R = 1 ,8039    ,213.4,213.6,213.4
XS GIS Cut Line= 4
2191590.58807878639779.3502814142191429.79620602640044.921733863
2191438.21189227 640078.584478872191396.56636317640178.493413607
#Sta/Elev= 30
       0 2102.27    25.5 2091.42    35.6 2088.61    43.3 2085.53    58.3 2080.49
   100.3 2069.87   114.4 2068.73   142.9 2064.42   156.4 2063.26   198.5 2063.44
   217.2 2060.84   226.6 2060.25   253.6 2061.28   259.4 2059.96   265.2 2057.37
   268.7 2056.49   273.3 2056.32   282.7 2057.31   290.4 2058.68   305.9 2060.36
   322.5  2059.8   331.3 2060.59   352.3  2060.7     361  2061.7   370.1 2065.81
   382.3 2072.11     387 2073.83   402.4 2078.42     426 2084.27   453.4 2091.92
#Mann= 3 ,-1,0
       0      .1       0   265.2    .045       0   282.7      .1       0
Bank Sta=265.2,282.7
XS Rating Curve= 0 ,0
Exp/Cntr(USF)=0,0
Exp/Cntr=0.3,0.1

Type RM Length L Ch R = 1 ,7825    ,122.6,123.1,122.5
XS GIS Cut Line= 2
2191403.28780727639682.8710960132191187.59787818 640034.03569131
#Sta/Elev= 30
       0 2099.02     9.8 2096.21    30.9 2086.44    49.7 2081.06      59 2077.28
    73.7 2072.62    82.5 2068.81   123.2 2061.62   129.5 2058.75   134.1 2055.68
   138.8 2053.72   148.2 2053.41   158.8 2055.83     167 2055.72   195.9 2057.16
   209.3 2056.77   223.3 2053.96   230.8 2053.47   239.5  2052.8   253.1 2053.47
   256.2 2054.53   265.6 2060.28   270.3 2062.03   283.1 2063.06   307.8 2067.16
   326.6 2068.88   364.2 2077.25   376.2 2081.13   395.7 2085.92   412.1 2091.25
#Mann= 3 ,-1,0
       0      .1       0   230.8    .045       0   253.1      .1       0
#XS Ineff= 2 , 0
          162.27 2060.37
Permanent Ineff=
       F       F
Bank Sta=230.8,253.1
XS Rating Curve= 0 ,0
Exp/Cntr(USF)=0,0
Exp/Cntr=0.3,0.1

Type RM Length L Ch R = 1 ,7702    ,160.4,160,158.1
XS GIS Cut Line= 2
2191282.89580742639643.5750510782191107.74433731639942.752697324
#Sta/Elev= 30
       0 2088.07    11.1 2082.88    20.7 2079.38    29.7 2077.14    52.8 2069.28
    71.4 2064.94    86.3 2063.23    94.6 2062.66   103.8 2062.97   117.7 2061.46
   159.5 2060.89   168.7 2060.28   173.4 2059.28   182.6 2054.12   190.3 2051.84
     199 2050.71   209.3  2051.8   222.4 2054.17   227.1  2054.1   234.1 2053.07
     237 2053.33   242.9 2055.39   247.5 2058.29   250.8 2059.61   258.7 2060.33
   270.7 2060.44   284.6 2062.24   298.8 2064.95   326.3 2071.35   346.7 2077.09
#Mann= 3 ,-1,0
       0      .1       0   190.3    .045       0   209.3      .1       0
Bank Sta=190.3,209.3
XS Rating Curve= 0 ,0
Exp/Cntr(USF)=0,0
Exp/Cntr=0.3,0.1

Type RM Length L Ch R = 1 ,7542    ,266.1,260.9,253.9
XS GIS Cut Line= 2
2191138.67302953639563.2223412952190970.32000865639892.005887936
#Sta/Elev= 30
       0 2086.07     6.3 2085.29     9.3 2084.42    20.2 2080.14    30.1 2077.26
    47.1 2070.93    56.1  2068.4    74.1 2061.74    87.6 2058.48    95.4 2057.37
   110.1 2057.07   137.1 2052.41     146 2052.21     164 2053.46   178.7 2053.15
     182 2052.62   186.4 2050.81   193.5 2045.94  196.632044.445   202.4 2043.59
   211.4 2044.46   222.4 2047.09   235.9 2051.31     244 2052.83     250 2053.52
   267.3  2053.6   285.3 2055.22   316.8 2059.99   339.5 2065.25   369.4 2075.25
#Mann= 3 ,-1,0
       0      .1       0  196.63    .045       0   211.4      .1       0
Bank Sta=196.63,211.4
XS Rating Curve= 0 ,0
Exp/Cntr(USF)=0,0
Exp/Cntr=0.3,0.1

Type RM Length L Ch R = 1 ,7281    ,200.9,207.5,211.8
XS GIS Cut Line= 3
2190960.04904359639513.8682867252190797.20551462639645.468580485
2190800.04580873 639827.24740352
#Sta/Elev= 30
       0 2069.16      18 2062.35    33.6 2057.74      41 2055.14    56.2  2050.9
    66.7 2048.77    87.3  2046.2    97.6 2046.16   118.9 2043.42   138.9  2041.4
   151.6 2041.32   159.3 2041.83   177.1 2041.33   196.2 2038.34   205.6 2037.73
   229.1 2037.86   237.1 2036.04   245.1 2035.45  250.612036.031   257.1 2037.89
   265.1 2038.56   281.1 2038.74   301.1 2037.87   313.1 2038.06   325.1 2038.89
   329.1 2039.57   341.1 2044.06   357.1 2054.21   376.7 2062.76   391.2 2067.07
#Mann= 3 ,-1,0
       0      .1       0   237.1    .045       0  250.61      .1       0
Bank Sta=237.1,250.61
XS Rating Curve= 0 ,0
Exp/Cntr(USF)=0,0
Exp/Cntr=0.3,0.1

Type RM Length L Ch R = 1 ,7074    ,303.8,302,293.2
XS GIS Cut Line= 2
2190796.22317884639350.899472621 2190539.5343376639898.145821638
#Sta/Elev= 30
       0  2084.6    15.8  2082.1    31.8 2078.03    55.5 2068.38    90.9    2057
   117.4 2050.92   128.1  2046.7   141.4 2044.53   148.3 2040.66   158.1 2033.77
   164.2 2031.05   173.2  2030.4   194.2 2032.47   212.3 2032.57   218.3 2031.53
  225.862028.098   236.3 2027.44   242.3  2028.1   263.2 2028.45     272 2030.91
   284.5 2032.83   294.1 2035.83     325 2035.36   338.6 2036.08   471.1 2049.08
     516 2055.47   546.4 2058.22   585.2 2067.22   594.2 2070.44   604.5 2072.68
#Mann= 4 ,-1,0
       0      .1       0  225.86    .045       0   242.3      .1       0
     500     .05       0
Bank Sta=225.86,242.3
XS Rating Curve= 0 ,0
Exp/Cntr(USF)=0,0
Exp/Cntr=0.3,0.1