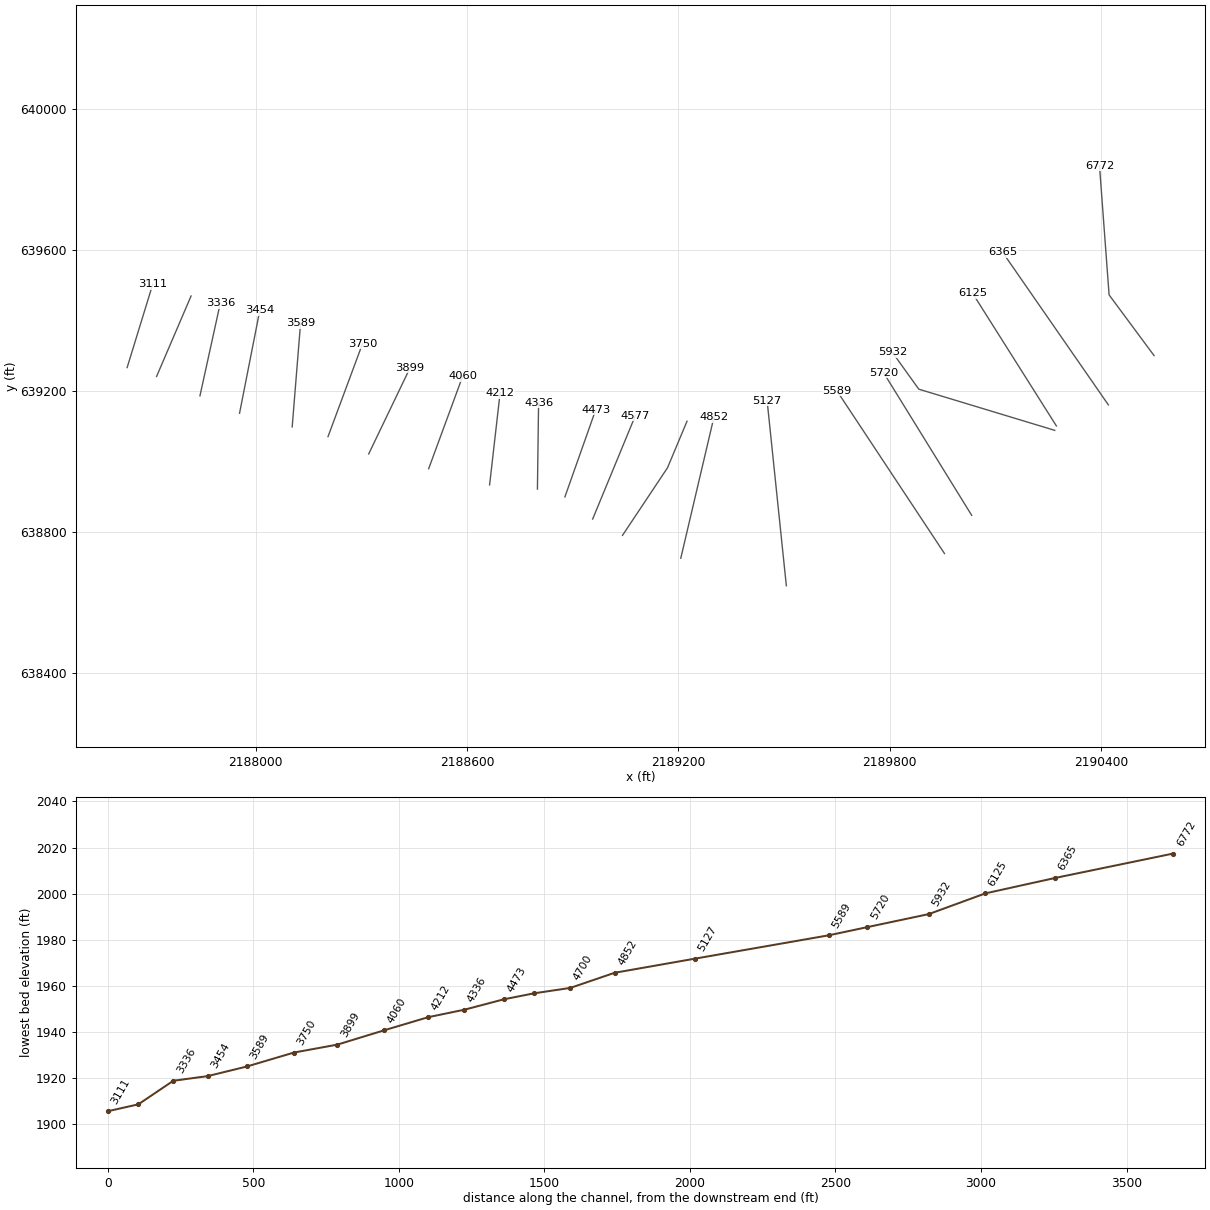
HEC-RAS study MILLSITERN.prj: MILLSITERN

--- MILLSITERN.g01 (geometry) --- (continued)

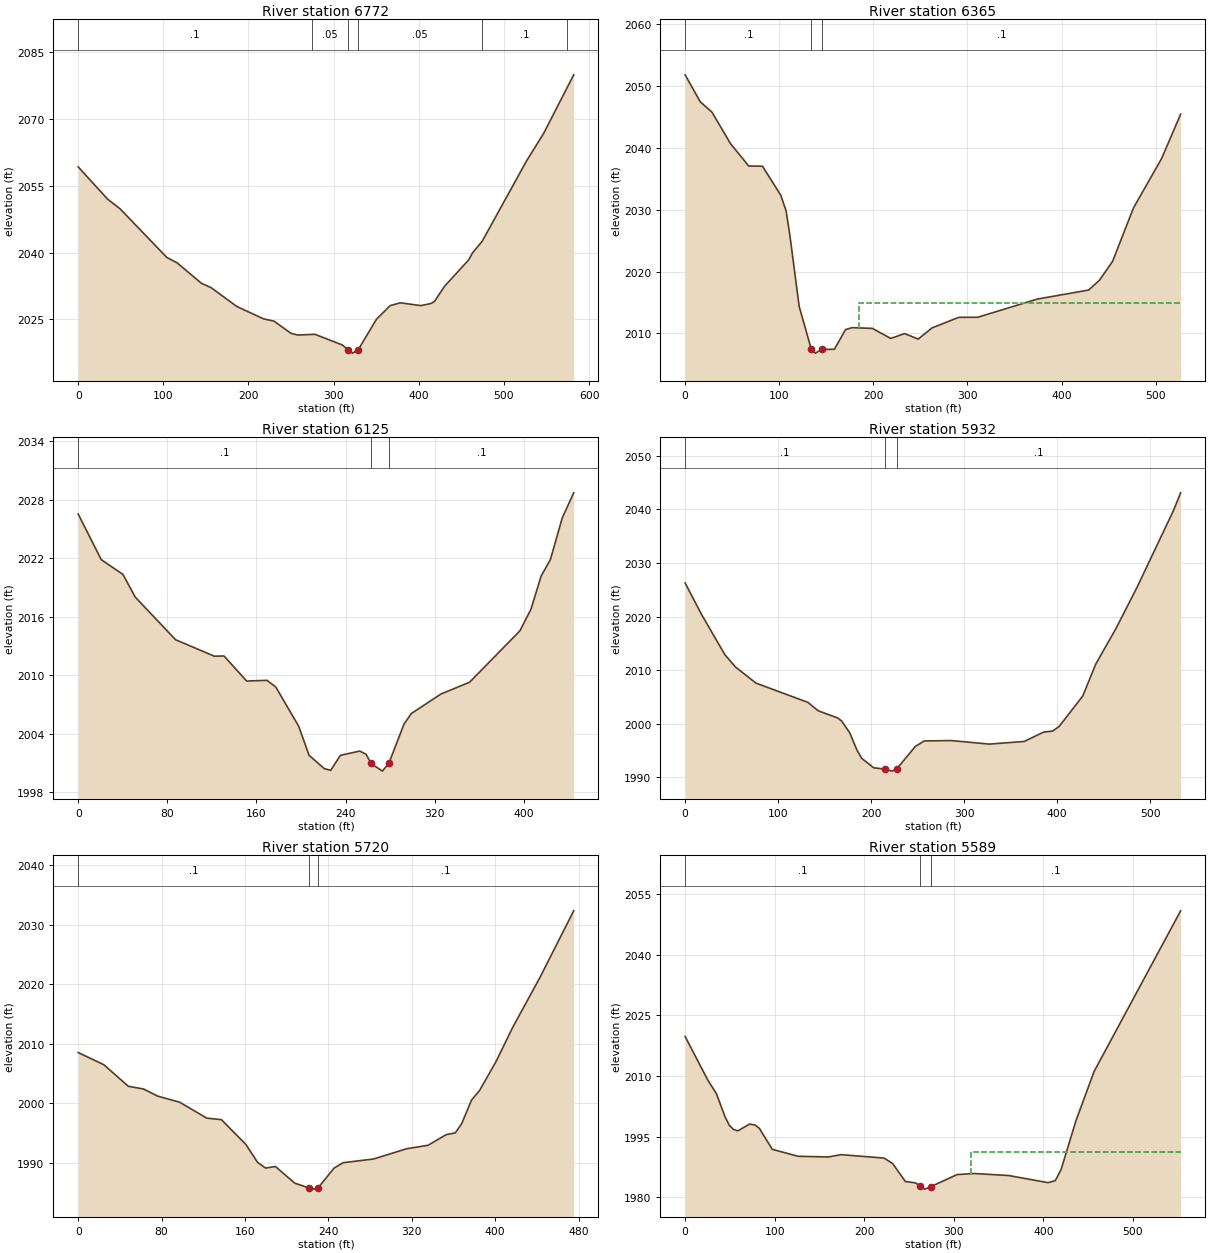
Type RM Length L Ch R = 1 ,6772    ,402.6,407.4,402.4
XS GIS Cut Line= 3
2190551.08789095639301.5203366612190423.36914939639473.822721338
2190396.07991695639840.278128303
#Sta/Elev= 30
       0 2059.27    34.4 2052.05    49.4 2049.81   104.1 2038.93   116.2 2037.71
   144.8 2033.12   156.3 2032.12   186.3 2027.91   217.8 2025.13   229.9 2024.63
   249.9 2021.89   257.9  2021.5     278 2021.67     310 2019.29  317.142018.177
   322.1 2017.44   328.8 2018.18   350.2 2025.02   366.3  2028.1   378.3 2028.74
   402.4 2028.11   414.4 2028.59   418.4 2029.04   430.4 2032.49   458.5 2038.36
   463.2 2039.97   474.6 2042.61   526.7 2060.66   546.8 2066.84   581.9 2079.94
#Mann= 6 ,-1,0
       0      .1       0  274.48     .05       0  317.14    .045       0
   328.8     .05       0  474.48      .1       0  574.48     .05       0
Bank Sta=317.14,328.8
XS Rating Curve= 0 ,0
Exp/Cntr(USF)=0,0
Exp/Cntr=0.3,0.1

Type RM Length L Ch R = 1 ,6365    ,242.3,239.1,232.9
XS GIS Cut Line= 2
2190421.33992741639161.6718170932190121.21551646639594.343286506
#Sta/Elev= 30
       0 2051.83    16.1 2047.46    28.6 2045.78    48.1 2040.73    67.6 2037.08
    82.2 2037.05   101.6 2032.37   107.3 2029.83   111.4 2025.79   121.2 2014.36
  134.172007.408   138.5 2006.82   145.4 2007.43   158.6 2007.44   170.5 2010.63
   177.5 2010.94     199 2010.82   218.5  2009.2   233.3 2009.98   247.7 2009.09
   262.3 2010.89   290.8 2012.61     311 2012.62   374.2 2015.56   428.8 2017.02
   440.3  2018.6   454.3 2021.67   476.5 2030.31   506.4  2038.3   526.6 2045.46
#Mann= 3 ,-1,0
       0      .1       0  134.17    .045       0   145.4      .1       0
#XS Ineff= 2 , 0
                          185.24         2014.87
Permanent Ineff=
       F       F
Bank Sta=134.17,145.4
XS Rating Curve= 0 ,0
Exp/Cntr(USF)=0,0
Exp/Cntr=0.3,0.1

Type RM Length L Ch R = 1 ,6125    ,185.8,193.9,204.5
XS GIS Cut Line= 2
2190273.64463369639102.0256407852190036.00669316639477.891227999
#Sta/Elev= 30
       0 2026.53    20.7 2021.85    40.2 2020.33    51.1 2018.02    87.4 2013.63
   122.2 2011.94   130.9 2011.96   151.2 2009.39   169.4 2009.46   177.3 2008.78
   197.8 2004.77   207.2 2001.77   220.8  2000.4   226.6 2000.22   235.3 2001.76
   252.7  2002.2   258.5 2001.86   262.7 2000.94     273 2000.14  278.882000.956
   292.4 2004.97   299.1 2006.06   325.5 2008.05   351.3 2009.27   396.5 2014.55
   406.4 2016.78   415.5 2020.17   423.8 2021.86   434.4 2026.12   444.7 2028.71
#Mann= 3 ,-1,0
       0      .1       0   262.7    .045       0  278.88      .1       0
Bank Sta=262.7,278.88
XS Rating Curve= 0 ,0
Exp/Cntr(USF)=0,0
Exp/Cntr=0.3,0.1

Type RM Length L Ch R = 1 ,5932    ,216,211.4,199
XS GIS Cut Line= 3
2190269.03320103639089.4945615532189882.81156492639206.351364275
2189807.54786147639311.324424347
#Sta/Elev= 30
       0 2026.26    17.6 2020.41    42.7  2012.9    54.2 2010.59    76.1  2007.6
     132    2004     143 2002.44   163.9  2001.1   168.1 2000.56   176.9 1998.34
   184.8 1995.08   189.7 1993.59   202.6 1991.81  214.741991.553   222.4 1991.18
  227.311991.561   247.5 1995.79   257.1 1996.81     286 1996.88   326.9 1996.22
   364.5 1996.71   385.4 1998.46   395.1 1998.65   402.1 1999.52   427.5 2005.19
   441.4 2011.12     463 2017.72   485.7 2025.41     525 2039.78   532.7 2043.08
#Mann= 3 ,-1,0
       0      .1       0  214.74    .045       0  227.31      .1       0
Bank Sta=214.74,227.31
XS Rating Curve= 0 ,0
Exp/Cntr(USF)=0,0
Exp/Cntr=0.3,0.1

Type RM Length L Ch R = 1 ,5720    ,131.3,131.5,131.9
XS GIS Cut Line= 2
2190033.16639905638848.2927002982189783.22051738639252.561228611
#Sta/Elev= 30
       0 2008.52    24.6 2006.47    48.1 2002.84    62.7 2002.38    76.3 2001.18
    97.3 2000.16   123.3 1997.48   137.4 1997.22   160.9 1993.04   172.1 1990.03
   179.7 1989.08   189.2 1989.34   207.7 1986.54   221.81985.703   226.8 1985.53
   230.1 1985.75   245.5 1989.08   254.2 1989.98   283.3  1990.6   315.2 1992.33
   335.6 1992.91     353  1994.7   361.7 1994.99   367.9 1996.56   377.3 2000.52
     385 2002.12   400.8    2007   416.9 2012.78   443.1 2021.21   475.3 2032.37
#Mann= 3 ,-1,0
       0      .1       0   221.8    .045       0   230.1      .1       0
Bank Sta=221.8,230.1
XS Rating Curve= 0 ,0
Exp/Cntr(USF)=0,0
Exp/Cntr=0.3,0.1

Type RM Length L Ch R = 1 ,5589    ,467,461.6,455.1
XS GIS Cut Line= 2
 2189955.8435015638740.0447903192189650.46399569639201.362767173
#Sta/Elev= 30
       0 2019.78    25.3    2009    34.9 2005.64    44.5 1999.92    49.3  1997.8
    54.1 1996.75    58.9 1996.43    71.9  1998.1    78.1 1997.87    82.9 1997.03
    97.3 1991.85   126.1 1990.13   159.7 1989.96   174.1 1990.53     222 1989.69
   231.6 1988.36   245.9 1983.88   257.5 1983.53  262.651982.661   267.5    1982
  274.551982.642   303.6  1985.6   322.8 1985.86   361.4 1985.36   405.2  1983.6
   413.3 1984.11   419.7 1986.84   436.4 1998.98   456.6 2011.13   553.2 2050.88
#Mann= 3 ,-1,0
       0      .1       0  262.65    .045       0  274.55      .1       0
#XS Ineff= 2 , 0
                          318.76         1991.27
Permanent Ineff=
       F       F
Bank Sta=262.65,274.55
XS Rating Curve= 0 ,0
Exp/Cntr(USF)=0,0
Exp/Cntr=0.3,0.1

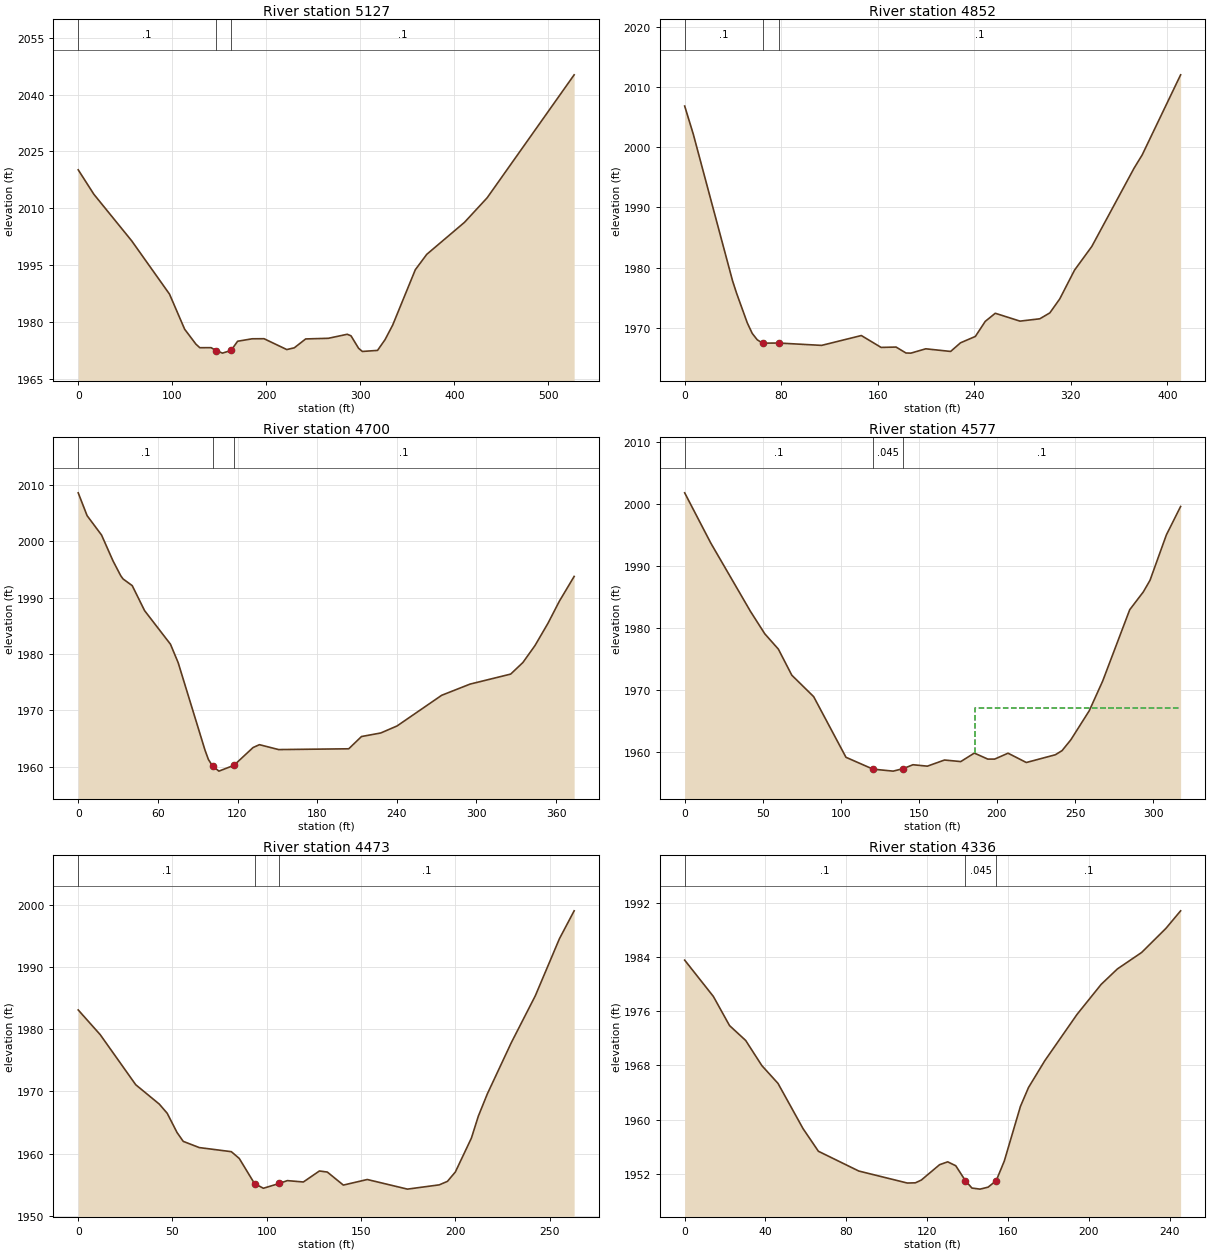
Type RM Length L Ch R = 1 ,5127    ,278.6,274.8,270.5
XS GIS Cut Line= 2
2189506.70371514638648.6144311452189452.15733638639173.222250415
#Sta/Elev= 30
       0 2020.16    16.7  2013.7    56.9 2001.43    97.1 1987.39   113.2 1978.14
   125.2  1974.2   129.3 1973.27   141.3 1973.28  146.72 1972.52   153.4 1971.84
  162.591972.556   169.5 1974.97     185 1975.62   197.6 1975.64   221.8 1972.78
   229.8 1973.24   241.9 1975.58     266 1975.75   286.1 1976.81   290.1  1976.4
   298.2  1973.1   302.2 1972.28   318.3 1972.56   326.3 1975.39   334.4 1979.22
   358.5 1993.83   370.7 1997.89   410.8 2006.32   434.9 2012.79   527.4  2045.2
#Mann= 3 ,-1,0
       0      .1       0  146.72    .045       0  162.59      .1       0
Bank Sta=146.72,162.59
XS Rating Curve= 0 ,0
Exp/Cntr(USF)=0,0
Exp/Cntr=0.3,0.1

Type RM Length L Ch R = 1 ,4852    ,156.3,152.4,148.4
XS GIS Cut Line= 2
2189206.90155656638726.6571295292189301.03044593 639126.70490935
#Sta/Elev= 30
       0  2006.9     7.1 2002.24    39.7 1977.77    43.1 1975.67    51.9 1970.77
      56 1969.02    60.1 1967.97    64.51967.405    78.11967.419   113.5 1967.03
   146.4 1968.67   162.8 1966.69   175.2 1966.75   183.4 1965.76   187.5 1965.74
   199.8 1966.46   220.4 1966.02   228.6 1967.46   240.9 1968.52   249.1 1971.03
   257.4 1972.38   277.9 1971.07   294.3 1971.46   302.6 1972.44   310.8 1974.76
   323.1 1979.57   337.4 1983.51   372.4 1996.54   379.1 1998.74     411  2012.1
#Mann= 3 ,-1,0
       0      .1       0    64.5    .045       0    78.1      .1       0
Bank Sta=64.5,78.1
XS Rating Curve= 0 ,0
Exp/Cntr(USF)=0,0
Exp/Cntr=0.3,0.1

Type RM Length L Ch R = 1 ,4700    ,120.4,123.2,125.5
XS GIS Cut Line= 3
  2189041.401916638791.5796475052189169.21515095638983.299499925
2189224.60088609639115.373176037
#Sta/Elev= 30
       0 2008.65     6.7 2004.59    17.6 2001.14    26.2 1996.56      32 1993.93
    33.8 1993.34    40.7 1992.15      50 1987.71    69.5 1981.74    75.3 1978.46
    95.5 1962.92    98.1 1961.24   101.2 1960.09     106 1959.18   117.3 1960.21
   131.7 1963.37   136.5 1963.88     151 1963.01   203.8 1963.15   213.4 1965.33
   227.9 1965.96   240.2 1967.21   273.8 1972.66   295.2 1974.65   325.8 1976.43
     335 1978.49   344.1  1981.5   353.9 1985.47   362.5  1989.4   373.6 1993.79
#Mann= 3 ,-1,0
       0      .1       0   101.2    .045       0   117.3      .1       0
Bank Sta=101.2,117.3
XS Rating Curve= 0 ,0
Exp/Cntr(USF)=0,0
Exp/Cntr=0.3,0.1

Type RM Length L Ch R = 1 ,4577    ,102.8,104,104.1
XS GIS Cut Line= 2
2188956.62688926638837.7483827442189077.87916857639131.259341139
#Sta/Elev= 30
       0 2001.73    16.7 1993.64    42.1 1982.63    51.3    1979      60 1976.53
    68.6 1972.33    82.6 1968.87   103.3 1959.09   120.6 1957.18   133.5 1956.86
   139.9 1957.26   146.2 1957.89   155.4 1957.66   166.4 1958.65   176.8  1958.4
   185.5 1959.77   194.1  1958.8   198.5  1958.8   207.1 1959.75   218.8 1958.25
   237.4  1959.5   241.7 1960.17   247.3 1961.91   259.1  1966.6   267.7 1971.39
     285 1982.88   293.7 1985.75     298 1987.63   308.5 1994.96   317.6 1999.53
#Mann= 3 ,-1,0
       0      .1       0   120.6    .045       0   139.9      .1       0
#XS Ineff= 2 , 0
                          185.75         1966.97
Permanent Ineff=
       F       F
Bank Sta=120.6,139.9
XS Rating Curve= 0 ,0
Exp/Cntr(USF)=0,0
Exp/Cntr=0.3,0.1

Type RM Length L Ch R = 1 ,4473    ,132.9,136.3,140.7
XS GIS Cut Line= 2
2188877.80097527638900.6469413262188965.56606326639148.604617123
#Sta/Elev= 30
       0 1983.13    11.7 1979.14    30.5 1971.09      43 1967.97    47.2 1966.49
    52.4  1963.4    55.7 1961.97    64.2 1960.97    81.2 1960.31    85.4 1959.22
    93.51955.173    98.2 1954.42   106.6 1955.19   110.9 1955.65   119.4 1955.43
   127.9  1957.2   132.1 1957.03   140.6 1954.93   153.3 1955.83   174.6 1954.28
   191.5 1954.97   195.8 1955.53     200 1957.04   208.5 1962.49   212.2 1966.04
     217 1969.64   229.7 1977.88   242.4 1985.41   255.2  1994.6     263 1999.09
#Mann= 3 ,-1,0
       0      .1       0    93.5    .045       0   106.6      .1       0
Bank Sta=93.5,106.6
XS Rating Curve= 0 ,0
Exp/Cntr(USF)=0,0
Exp/Cntr=0.3,0.1

Type RM Length L Ch R = 1 ,4336    ,125.1,124.2,122.8
XS GIS Cut Line= 2
2188799.77140002638922.9635504562188803.07268327639168.480196542
#Sta/Elev= 30
       0 1983.55    14.2 1978.19    22.2 1973.89    30.2 1971.69    38.2 1967.98
    46.2 1965.35    58.6 1958.67    66.2 1955.33    86.2 1952.41   110.2 1950.64
   114.2 1950.67   117.1 1951.07   126.2 1953.35   130.2 1953.77   134.2 1953.19
     1391950.972   142.2  1949.9   146.2 1949.74   150.2 1950.03   154.2 1950.98
   158.2 1953.87   166.2 1961.95   170.2 1964.74   178.2 1968.67   194.2 1975.53
   206.2 1979.98   214.2 1982.25   226.2 1984.68   238.2 1988.23   245.5 1990.83
#Mann= 3 ,-1,0
       0      .1       0     139    .045       0   154.2      .1       0
Bank Sta=139,154.2
XS Rating Curve= 0 ,0
Exp/Cntr(USF)=0,0
Exp/Cntr=0.3,0.1

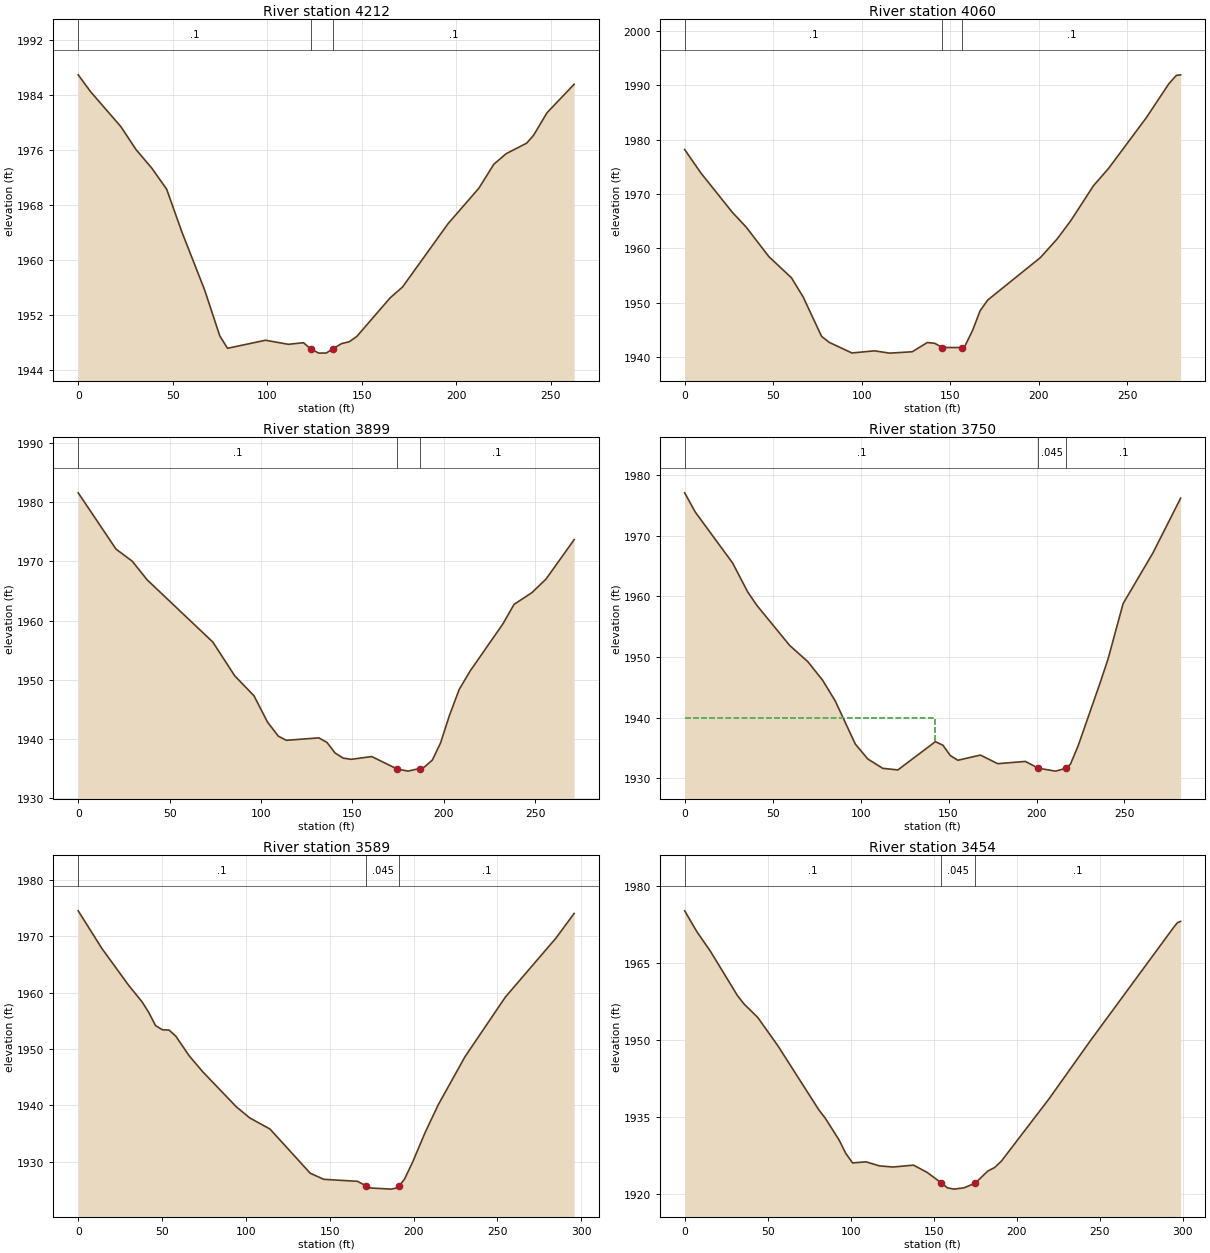
Type RM Length L Ch R = 1 ,4212    ,154.7,152.5,149
XS GIS Cut Line= 2
2188663.92682879638934.7304706462188693.74991694639195.469469937
#Sta/Elev= 30
       0  1986.9     6.5 1984.47    22.6 1979.37    30.6 1976.05    38.9 1973.37
    46.8  1970.3    54.8 1964.13    66.9 1955.67    74.9 1949.02      79 1947.21
    99.1 1948.38   111.2 1947.79   119.2 1948.02     1231947.127   127.3 1946.51
   131.3 1946.53  134.881947.164   139.4  1947.9   143.4 1948.16   147.4 1948.93
     165 1954.52   171.6 1956.11   195.7  1965.3     212 1970.45   219.9 1973.92
   226.4 1975.45   237.3 1976.99   240.9 1978.11   248.1 1981.42   262.4 1985.53
#Mann= 3 ,-1,0
       0      .1       0     123    .045       0  134.88      .1       0
Bank Sta=123,134.88
XS Rating Curve= 0 ,0
Exp/Cntr(USF)=0,0
Exp/Cntr=0.3,0.1

Type RM Length L Ch R = 1 ,4060    ,161,160.3,159.1
XS GIS Cut Line= 2
2188490.87638075638980.6345126512188587.61598779639243.419713864
#Sta/Elev= 30
       0 1978.17     9.1 1973.89    26.9 1966.65    34.7 1963.94    47.5 1958.52
    60.3 1954.61    66.9 1951.09    77.3 1943.86    81.6 1942.76    94.4 1940.81
   107.1  1941.2   115.7 1940.78   128.5 1941.03     137 1942.73   141.2 1942.58
   145.5 1941.81  156.521941.803   158.3 1942.12   162.6 1944.99   166.8 1948.56
   171.1 1950.53   200.9 1958.35   210.2 1961.72     218 1965.11   230.8 1971.53
   239.3  1974.7   260.6 1984.01   273.4 1990.28   277.6  1991.8     280  1991.9
#Mann= 3 ,-1,0
       0      .1       0   145.5    .045       0  156.52      .1       0
Bank Sta=145.5,156.52
XS Rating Curve= 0 ,0
Exp/Cntr(USF)=0,0
Exp/Cntr=0.3,0.1

Type RM Length L Ch R = 1 ,3899    ,146.7,148.7,149.6
XS GIS Cut Line= 2
 2188320.5352709639022.4955586422188438.12344705639267.044881507
#Sta/Elev= 30
       0 1981.54    20.7 1972.04    29.6    1970    37.7 1966.87    73.7 1956.35
    85.7 1950.65    96.2  1947.3   103.6 1942.86   109.5 1940.49   113.9 1939.79
   131.7  1940.2   136.1 1939.44   140.6 1937.64     145 1936.79   149.4 1936.58
   160.6 1937.05   174.5 1934.96   180.5 1934.59   186.8 1935.03   189.4 1935.27
   193.8 1936.46   198.3 1939.35   203.1 1943.94   208.5 1948.38   214.5 1951.49
   232.5 1959.47   238.5 1962.72   248.4 1964.73     256 1966.99   271.4 1973.64
#Mann= 3 ,-1,0
       0      .1       0   174.5    .045       0   186.8      .1       0
Bank Sta=174.5,186.8
XS Rating Curve= 0 ,0
Exp/Cntr(USF)=0,0
Exp/Cntr=0.3,0.1

Type RM Length L Ch R = 1 ,3750    ,157.6,161.8,164.7
XS GIS Cut Line= 2
2188204.98918383639071.598620763 2188303.1726656639335.827696708
#Sta/Elev= 30
       0 1977.06       6  1973.9    27.3 1965.47    35.8 1960.73      41 1958.51
    59.7 1951.89      70 1949.22    78.4 1946.16    85.6 1942.73      97 1935.63
   104.1 1933.17   112.6 1931.63   121.2 1931.37   142.5 1936.03   146.8 1935.44
     151 1933.74   155.3 1932.96   168.1 1933.82   177.9  1932.4   193.7 1932.77
     201 1931.65   210.8 1931.17  216.821931.637   219.3 1932.34   223.6  1935.3
   236.4 1945.94   240.7 1949.71   249.2 1958.79   266.3 1967.22   281.9 1976.18
#Mann= 3 ,-1,0
       0      .1       0     201    .045       0  216.82      .1       0
#XS Ineff= 2 , 0
          142.48 1939.93
Permanent Ineff=
       F       F
Bank Sta=201,216.82
XS Rating Curve= 0 ,0
Exp/Cntr(USF)=0,0
Exp/Cntr=0.3,0.1

Type RM Length L Ch R = 1 ,3589    ,136.3,134.7,133
XS GIS Cut Line= 2
2188103.25277149639099.1834996112188127.11124201639394.006028221
#Sta/Elev= 30
       0 1974.55      14 1967.92    30.1 1961.31    38.1 1958.38    42.1  1956.5
    46.1 1954.17    50.2 1953.43    54.2 1953.37    58.2 1952.29    66.2  1948.8
    74.2 1945.99    94.3 1939.74   102.3 1937.77   114.4 1935.79   138.4 1927.94
   146.5 1926.86   166.5 1926.51   171.8 1925.69   174.6 1925.32   186.6 1925.12
   190.6 1925.36  191.391925.662   194.6 1926.89   199.5 1929.95   206.9 1935.17
   214.7 1940.08   230.7 1948.64   254.8 1959.24   284.9 1969.69   295.8 1974.09
#Mann= 3 ,-1,0
       0      .1       0   171.8    .045       0  191.39      .1       0
Bank Sta=171.8,191.39
XS Rating Curve= 0 ,0
Exp/Cntr(USF)=0,0
Exp/Cntr=0.3,0.1

Type RM Length L Ch R = 1 ,3454    ,118,118,117.3
XS GIS Cut Line= 2
2187953.75498047639138.0168584322188011.50996975639431.123429015
#Sta/Elev= 30
       0 1975.21     7.3 1971.17    15.5 1967.33    31.8 1958.68    35.8 1957.03
      44 1954.43    56.2 1948.87    80.7 1936.46    84.8 1934.72    92.9 1930.58
      97 1927.94   101.1 1926.06   109.2 1926.27   117.4 1925.48   125.5 1925.26
   137.8 1925.63   145.9 1924.24   154.6 1922.16   158.1 1921.22   162.2 1920.95
   168.2  1921.2     175 1922.12   182.6 1924.48   186.7 1925.17   190.8 1926.43
   219.3 1938.49   243.8 1949.64   294.2 1971.85   296.8 1972.91   298.7 1973.15
#Mann= 3 ,-1,0
       0      .1       0   154.6    .045       0     175      .1       0
Bank Sta=154.6,175
XS Rating Curve= 0 ,0
Exp/Cntr(USF)=0,0
Exp/Cntr=0.3,0.1

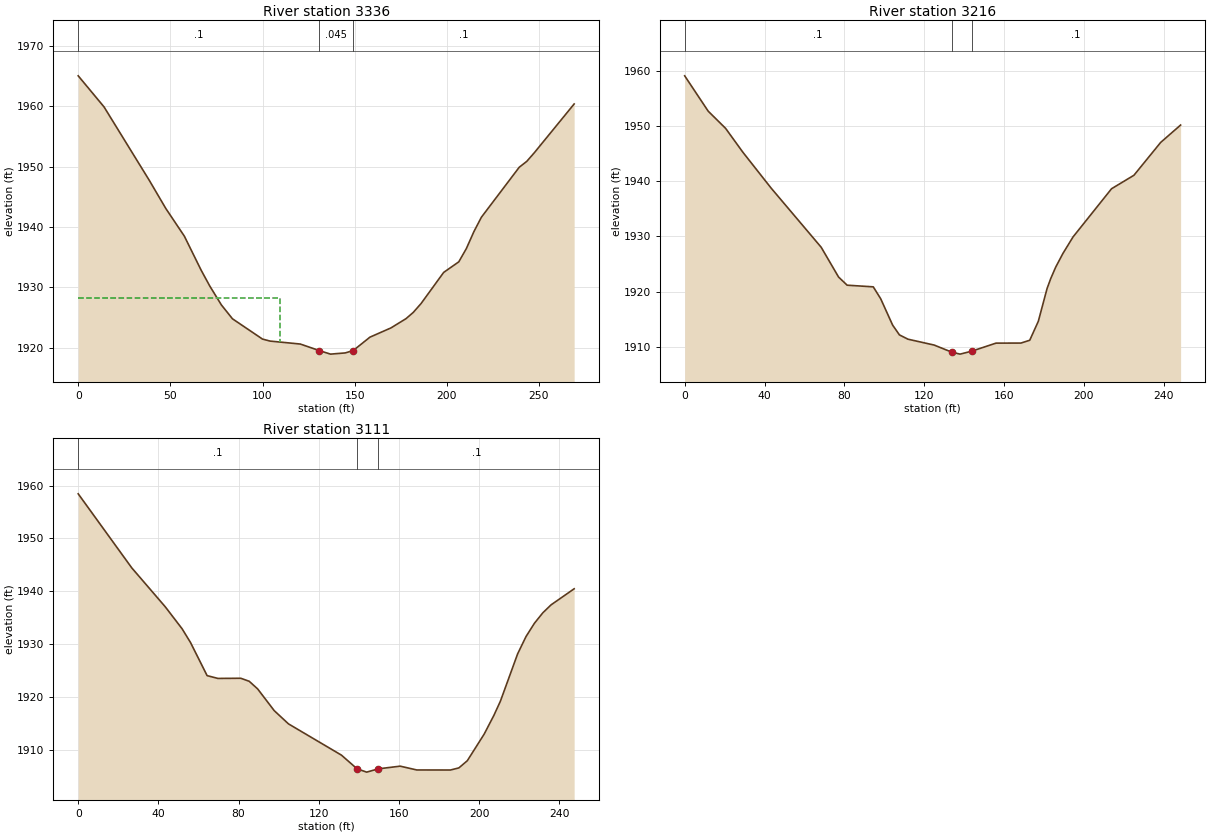
Type RM Length L Ch R = 1 ,3336    ,121.3,120.2,115
XS GIS Cut Line= 2
2187841.29461555639187.4788438282187899.09305639639450.324134319
#Sta/Elev= 30
       0 1965.02      14 1959.88    38.6  1947.7    47.5 1943.07    57.6 1938.47
    66.7 1932.84    71.4 1930.21    77.7 1927.08    83.7 1924.79     100 1921.43
   104.1  1921.1   120.5 1920.61   130.91919.521   136.9 1918.94   144.9 1919.14
   149.2 1919.53   158.3 1921.75   169.7 1923.28   177.9 1924.82   181.8 1925.85
     186  1927.3   198.3 1932.47   206.5 1934.22   210.6 1936.41   214.7 1939.22
   218.8 1941.62   239.3 1949.88   243.4 1950.86   247.5 1952.29   269.1 1960.36
#Mann= 3 ,-1,0
       0      .1       0   130.9    .045       0   149.2      .1       0
#XS Ineff= 2 , 0
          109.24 1928.19
Permanent Ineff=
       F       F
Bank Sta=130.9,149.2
XS Rating Curve= 0 ,0
Exp/Cntr(USF)=0,0
Exp/Cntr=0.3,0.1

Type RM Length L Ch R = 1 ,3216    ,103.5,105,105.8
XS GIS Cut Line= 2
2187718.10889018639242.3343227512187816.09903698 639470.69396919
#Sta/Elev= 30
       0 1959.06    11.8 1952.66    20.5 1949.56    29.2 1945.22    43.3 1938.76
    68.4 1928.05    77.1 1922.67    81.4 1921.19    94.5 1920.89    98.2 1918.75
   104.2 1913.97   107.6  1912.2   111.9 1911.42     125 1910.36   133.81909.081
     138 1908.72   143.8 1909.25     156 1910.71   168.5 1910.72   172.9 1911.23
   177.2 1914.66   181.6  1920.6   183.4 1922.37   185.9 1924.45   189.5 1926.91
   194.6 1929.92   213.9 1938.64   225.1 1941.07   238.5 1947.01   248.5 1950.16
#Mann= 3 ,-1,0
       0      .1       0   133.8    .045       0   143.8      .1       0
Bank Sta=133.8,143.8
XS Rating Curve= 0 ,0
Exp/Cntr(USF)=0,0
Exp/Cntr=0.3,0.1

Type RM Length L Ch R = 1 ,3111    ,131.4,131,130.1
XS GIS Cut Line= 2
2187634.51427724 639267.676809362187707.28556373639504.183490451
#Sta/Elev= 30
       0 1958.44    26.7 1944.42    43.4 1937.05    51.8 1932.89      56 1930.29
    64.3    1924    69.7 1923.47    81.1  1923.5    85.3 1922.93    89.5 1921.49
    97.8 1917.36   104.9 1914.86   131.3 1908.94  139.131906.344   143.9 1905.72
  149.731906.342   160.6 1906.85   168.9 1906.13   185.7 1906.12   189.9 1906.52
   194.1 1907.88   202.5 1912.91   207.4  1916.5   210.6 1919.15   219.2 1928.12
   223.4 1931.41   227.6 1933.93   231.8 1935.91   235.9 1937.41   247.4 1940.45
#Mann= 3 ,-1,0
       0      .1       0  139.13    .045       0  149.73      .1       0
Bank Sta=139.13,149.73
XS Rating Curve= 0 ,0
Exp/Cntr(USF)=0,0
Exp/Cntr=0.3,0.1