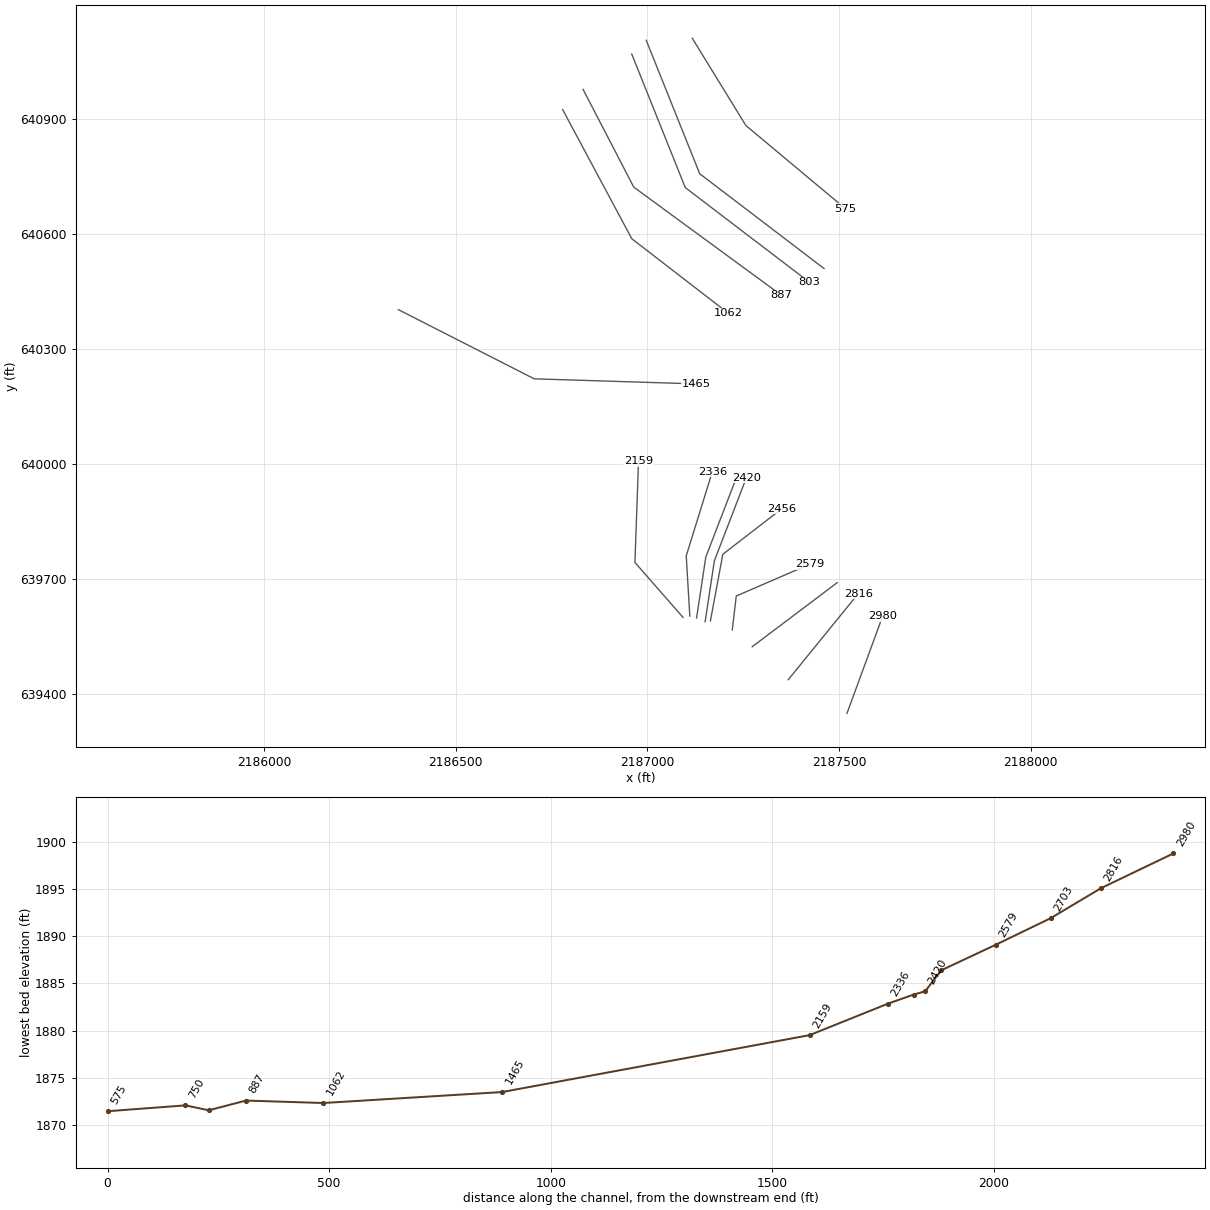
HEC-RAS study MILLSITERN.prj: MILLSITERN

--- MILLSITERN.g01 (geometry) --- (continued)

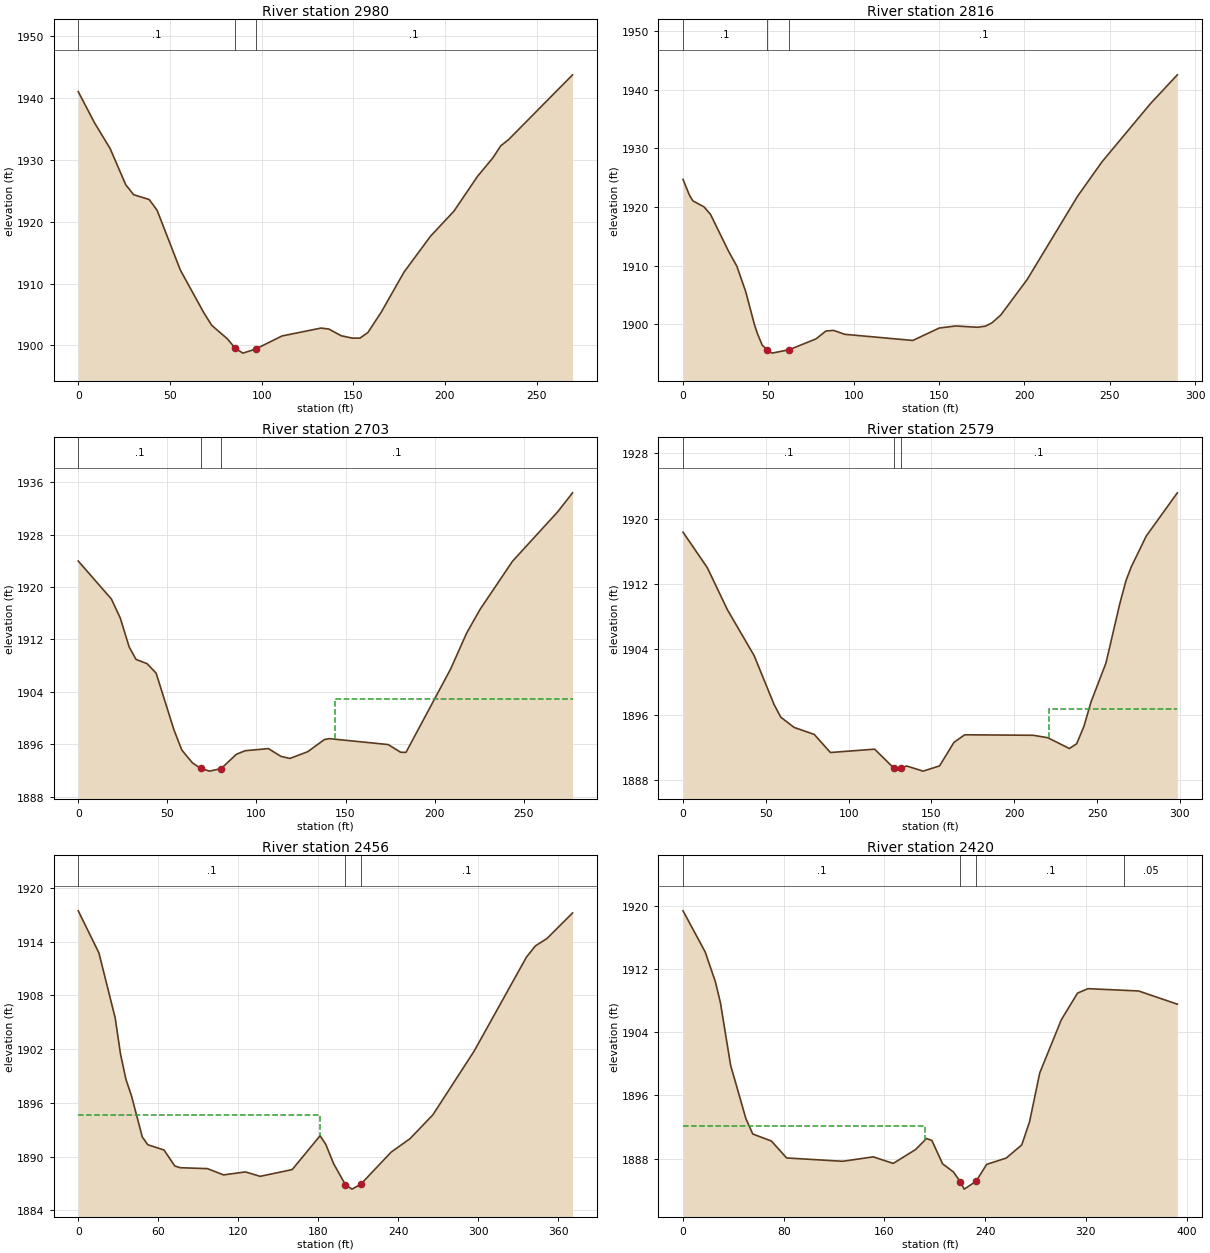
Type RM Length L Ch R = 1 ,2980    ,165.9,163.5,159.4
XS GIS Cut Line= 2
2187520.42442013639348.8453518742187613.30203753639601.915557068
#Sta/Elev= 30
       0    1941     8.9 1935.95    17.4  1931.8    25.9 1925.96    30.2 1924.35
    38.7 1923.57      43 1921.84    55.7 1912.16    68.5 1905.27    72.8 1903.24
    81.3 1901.07    85.71899.511    89.8 1898.75    96.7  1899.4   111.1 1901.52
   132.4  1902.8   136.7 1902.64   143.4 1901.56   149.5 1901.17   153.7 1901.18
     158 1902.09   165.3 1905.39   177.7 1911.85   192.1 1917.63   204.9 1921.69
   217.7 1927.29   226.2 1930.33   230.4 1932.24   234.7 1933.25   269.6 1943.72
#Mann= 3 ,-1,0
       0      .1       0    85.7    .045       0    96.7      .1       0
Bank Sta=85.7,96.7
XS Rating Curve= 0 ,0
Exp/Cntr(USF)=0,0
Exp/Cntr=0.3,0.1

Type RM Length L Ch R = 1 ,2816    ,115.6,113.7,110.8
XS GIS Cut Line= 2
2187367.36037645639436.7102565382187550.04760542639661.421448759
#Sta/Elev= 30
       0 1924.69     3.8 1921.97     5.8 1921.03    12.3 1920.01    16.1 1918.73
    26.5 1912.54    31.5 1909.91    36.7 1905.58    41.8 1899.97    43.6 1898.39
    46.4 1896.43    49.3 1895.65    52.1 1895.07    62.21895.652    77.9  1897.5
    83.7 1898.84    88.2 1898.95    94.7 1898.28   134.6 1897.23   150.1 1899.35
   159.8  1899.7   172.5 1899.48   177.2 1899.67     181 1900.24   186.2 1901.58
   201.7 1907.66   231.2 1921.85   245.4 1927.67   273.8  1937.6   289.6 1942.53
#Mann= 3 ,0,0
       0      .1       0    49.3    .045       0    62.2      .1       0
Bank Sta=49.3,62.2
XS Rating Curve= 0 ,0
Exp/Cntr(USF)=0,0
Exp/Cntr=0.3,0.1

Type RM Length L Ch R = 1 ,2703    ,125.9,124,122.4
XS GIS Cut Line= 2
2187273.31883257639522.6713514012187494.86177314639689.680645065
#Sta/Elev= 30
       0 1923.98    18.6 1918.18    23.6 1915.26    28.6 1910.84    32.4 1908.96
    38.6 1908.31    43.7 1906.86    53.7  1898.2    58.1 1895.12      64 1893.18
    68.7  1892.3    73.7 1891.89   80.231892.284    88.7 1894.46    93.7 1895.01
   106.7 1895.33   113.8 1894.14   118.8 1893.83   128.8 1894.86   138.1 1896.71
   140.9 1896.85   173.9 1895.95   180.9 1894.78   183.9 1894.75     209  1907.5
     218    1913   225.6 1916.64   243.7 1923.95   269.1 1931.51   277.4  1934.4
#Mann= 3 ,-1,0
       0      .1       0    68.7    .045       0   80.23      .1       0
#XS Ineff= 2 , 0
                          144.17         1902.88
Permanent Ineff=
       F       F
Bank Sta=68.7,80.23
XS Rating Curve= 0 ,0
Exp/Cntr(USF)=0,0
Exp/Cntr=0.3,0.1

Type RM Length L Ch R = 1 ,2579    ,119.8,122.8,124.5
XS GIS Cut Line= 3
2187221.27732896639566.5588788712187231.67322703639654.924012465
2187423.99734133639738.091197025
#Sta/Elev= 30
       0 1918.34    14.7 1913.98    26.8 1908.84    42.9 1903.24      55 1897.23
      59 1895.69    67.1 1894.43    79.2 1893.58      89 1891.36   115.7 1891.77
  127.161889.483   128.7 1889.21   131.7 1889.49     135 1889.71     145 1889.08
   154.9 1889.72   163.6  1892.6   170.1 1893.53   211.5 1893.47   220.3 1893.17
   233.3 1891.85   237.7 1892.43   242.1 1894.57   246.4 1897.57   255.4 1902.32
   263.8 1909.62   267.5 1912.41   270.6 1914.06   279.7 1917.86   298.5 1923.16
#Mann= 3 ,-1,0
       0      .1       0  127.16    .045       0   131.7      .1       0
#XS Ineff= 2 , 0
                          220.79          1896.7
Permanent Ineff=
       F       F
Bank Sta=127.16,131.7
XS Rating Curve= 0 ,0
Exp/Cntr(USF)=0,0
Exp/Cntr=0.3,0.1

Type RM Length L Ch R = 1 ,2456    ,27.8,36.2,40.5
XS GIS Cut Line= 3
2187164.25153875639589.986321807 2187196.6308916639763.812321335
2187350.00677354639882.252585719
#Sta/Elev= 30
       0 1917.45    15.5 1912.75    27.7 1905.49    31.7 1901.45    35.8 1898.61
    39.9  1896.8      48 1892.21    52.1 1891.34    64.3 1890.75    72.4 1888.96
    76.5 1888.77    96.8 1888.67     109 1887.97   125.3  1888.3   136.4 1887.81
   160.4 1888.56   181.3 1892.34   185.6 1891.38   191.4 1889.24   200.3 1886.87
   205.2 1886.38   211.8 1886.92   234.5  1890.5   248.8 1892.02   265.9 1894.68
   296.9 1901.81   336.1  1912.3   342.7 1913.53   351.4 1914.36   370.6 1917.21
#Mann= 3 ,-1,0
       0      .1       0   200.3    .045       0   211.8      .1       0
#XS Ineff= 2 , 0
          181.18 1894.71
Permanent Ineff=
       F       F
Bank Sta=200.3,211.8
XS Rating Curve= 0 ,0
Exp/Cntr(USF)=0,0
Exp/Cntr=0.3,0.1

Type RM Length L Ch R = 1 ,2420    ,26.3,26.2,27.3
XS GIS Cut Line= 3
2187150.48296602 639587.795742162187174.54754489639746.621962673
2187257.97141829639963.203172464
#Sta/Elev= 30
       0 1919.34    17.6 1914.14    25.7 1910.37    29.7 1907.73    37.8 1899.82
    49.9 1893.09    55.4 1891.13    70.2 1890.24    82.3  1888.1   126.8 1887.68
   151.1 1888.24     167 1887.41   184.8 1889.17   193.4 1890.56   197.7 1890.31
   206.2 1887.36   214.8 1886.33  220.171885.116   223.4 1884.16  232.851885.161
   241.2 1887.29   256.7 1888.08   269.1 1889.75   275.3 1892.68   283.4 1898.86
   300.5 1905.56   313.4 1908.94   321.7  1909.5   361.9 1909.21   392.7 1907.54
#Mann= 4 ,-1,0
       0      .1       0  220.17    .045       0  232.85      .1       0
  350.64     .05       0
#XS Ineff= 2 , 0
          192.23 1892.14
Permanent Ineff=
       F       F
Bank Sta=220.17,232.85
XS Rating Curve= 0 ,0
Exp/Cntr(USF)=0,0
Exp/Cntr=0.3,0.1

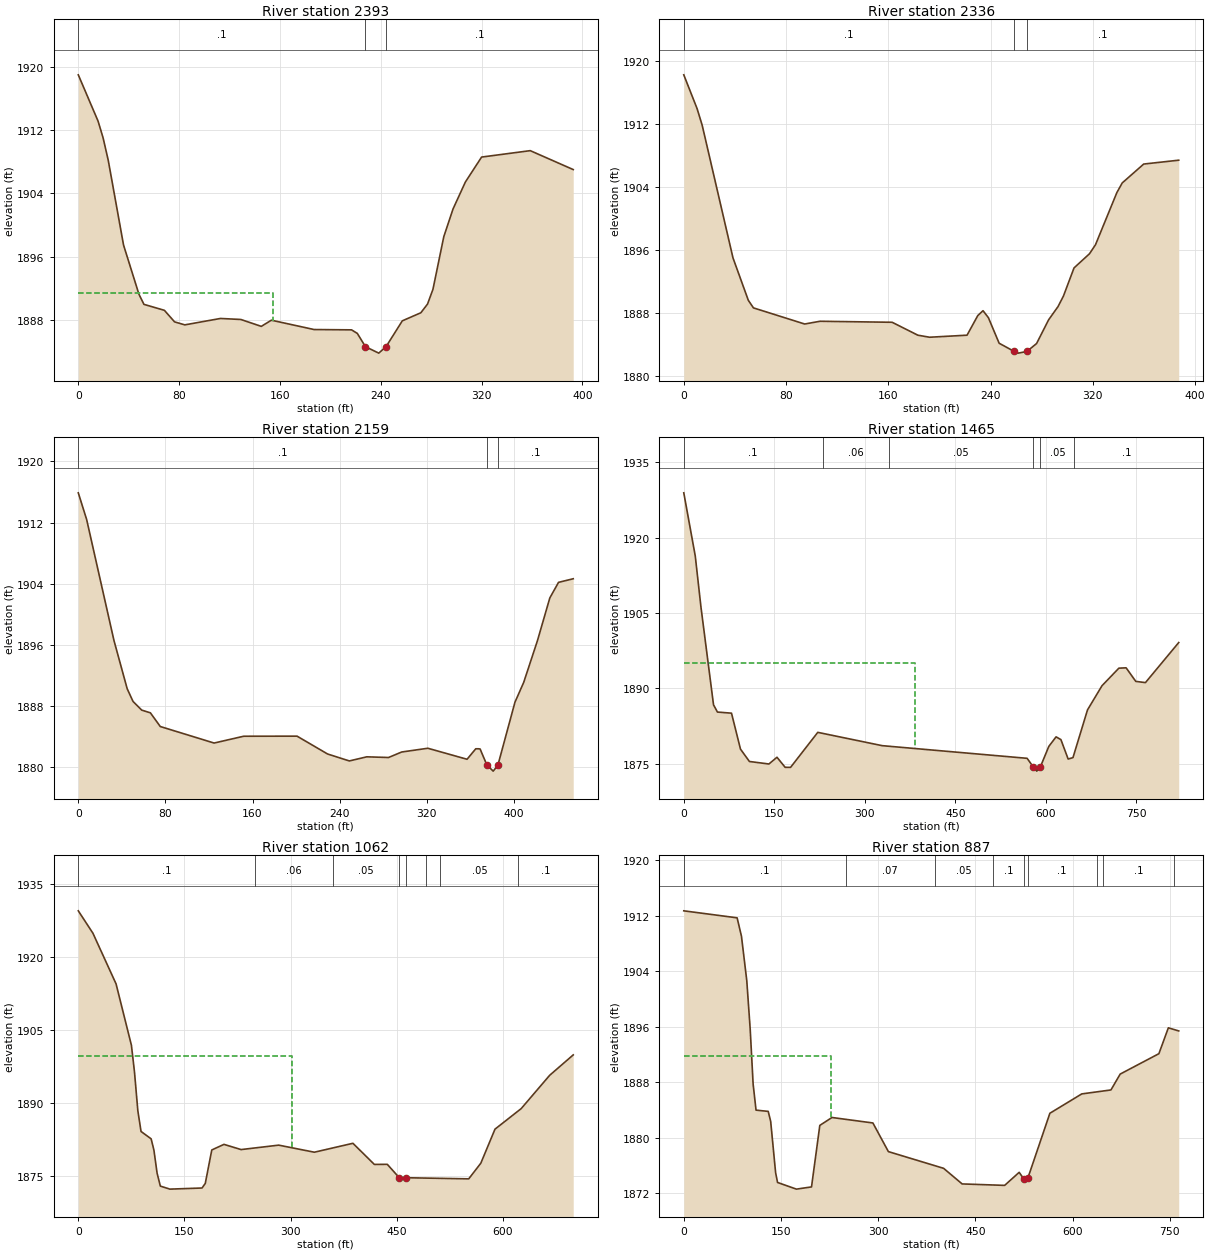
Type RM Length L Ch R = 1 ,2393    ,56.3,57.3,57.9
XS GIS Cut Line= 3
 2187128.1711054639597.6657911722187152.23568426639756.492011686
2187235.65955767639973.073221476
#Sta/Elev= 30
       0 1918.97    15.7 1913.12    19.7    1911    23.8 1908.15    35.9 1897.47
    48.1 1891.26    52.1 1889.97    68.3 1889.22    76.4 1887.76    84.5 1887.38
   112.8 1888.19     129 1888.06   145.2 1887.19   153.2 1887.97   187.1 1886.79
   216.8 1886.75   221.4  1886.3  227.841884.623   238.4 1883.81  244.211884.632
   257.1 1887.89   271.8 1888.91   277.1 1890.01   281.4 1891.87     290 1898.52
   297.3 1902.01   307.1 1905.42     320 1908.58   358.6 1909.39   392.7    1907
#Mann= 3 ,-1,0
       0      .1       0  227.84    .045       0  244.21      .1       0
#XS Ineff= 2 , 0
          154.82 1891.35
Permanent Ineff=
       F       F
Bank Sta=227.84,244.21
XS Rating Curve= 0 ,0
Exp/Cntr(USF)=0,0
Exp/Cntr=0.3,0.1

Type RM Length L Ch R = 1 ,2336    ,174.2,177.4,179.2
XS GIS Cut Line= 3
2187110.56998007639602.7676453022187101.19700951 639759.55188017
2187169.36406815639979.390644278
#Sta/Elev= 30
       0 1918.23    10.4 1913.94    14.4 1911.82    38.5 1894.96    50.5 1889.57
    54.5 1888.61    94.6 1886.56   106.6 1886.91     163 1886.78   183.1 1885.14
   192.3 1884.88   221.6 1885.14     230 1887.63   234.1 1888.25   238.3 1887.37
   246.7 1884.12   258.2  1883.1   261.7 1882.86   268.41883.068     276 1884.08
   285.4 1887.09   292.8 1888.78     297 1890.11   305.3 1893.69   317.4 1895.49
   322.1 1896.64   338.8 1903.26     343 1904.49   359.8 1906.89   387.2 1907.38
#Mann= 3 ,-1,0
       0      .1       0   258.2    .045       0   268.4      .1       0
Bank Sta=258.2,268.4
XS Rating Curve= 0 ,0
Exp/Cntr(USF)=0,0
Exp/Cntr=0.3,0.1

Type RM Length L Ch R = 1 ,2159    ,708.6,693.9,675.5
XS GIS Cut Line= 3
2187092.67612718 639599.359292372186967.41915693 639742.51011551
2186976.79212749640006.657467733
#Sta/Elev= 30
       0 1915.89     7.7 1912.39    32.8 1896.57    44.9 1890.29    50.3 1888.62
    58.3 1887.49    66.2 1887.14    75.3 1885.35   124.7 1883.19   151.9 1884.08
   200.9 1884.09   228.9 1881.76   248.9 1880.85   264.9 1881.39   284.9  1881.3
     297 1882.02     321 1882.51     357 1881.07     365 1882.44   367.5 1882.44
     369 1882.41   375.2 1880.32     381 1879.52   385.31880.287     401 1888.53
     409 1891.11   421.6 1896.55     433 1902.15     441 1904.19   454.5 1904.66
#Mann= 3 ,-1,0
       0      .1       0   375.2    .045       0   385.3      .1       0
Bank Sta=375.2,385.3
XS Rating Curve= 0 ,0
Exp/Cntr(USF)=0,0
Exp/Cntr=0.3,0.1

Type RM Length L Ch R = 1 ,1465    ,408.1,403,393.9
XS GIS Cut Line= 3
2186350.46259216640401.7984061032186704.77417856640221.341573274
2187127.30725055640208.137414775
#Sta/Elev= 30
       0 1928.91      19 1916.37    28.5 1906.14    49.3  1886.7    55.8 1885.26
    79.1 1885.04      94 1877.88   108.8 1875.42   141.1 1874.92   154.5 1876.26
     168 1874.26     177 1874.25   222.1 1881.22   328.9 1878.57   569.1 1876.05
   579.6 1874.29   585.1  1873.5  590.811874.273   605.1 1878.43   617.1 1880.32
   625.1 1879.78   637.1 1875.91   645.1 1876.19   669.2 1885.69   693.2  1890.5
   721.2    1894   733.2 1894.07   749.2 1891.37   765.2 1891.12   820.4  1899.1
#Mann= 6 ,-1,0
       0      .1       0     230     .06       0     340     .05       0
   579.6    .045       0  590.81     .05       0  647.62      .1       0
#XS Ineff= 2 , 0
          382.54 1895.02
Permanent Ineff=
       F       F
Bank Sta=579.6,590.81
XS Rating Curve= 0 ,0
Exp/Cntr(USF)=0,0
Exp/Cntr=0.3,0.1

Type RM Length L Ch R = 1 ,1062    ,173.7,174.8,171
XS GIS Cut Line= 3
2186778.99066606640923.4160993062186959.22742958640586.710057564
  2187210.766649640392.608927619
#Sta/Elev= 30
       0 1929.48    20.7 1924.88    53.4 1914.48    75.1 1901.88    79.4 1896.46
    84.2 1888.41    88.7 1884.18     103 1882.66   106.9 1880.35   111.4 1875.61
     116 1872.96   129.5 1872.34   174.9 1872.57   179.5 1873.51   188.7 1880.38
   205.9 1881.53   230.1 1880.46   283.3 1881.37   333.7 1879.92   388.2 1881.75
   418.5 1877.41   436.8 1877.43   453.8 1874.67     463 1874.68   551.9 1874.45
     569 1877.67     589 1884.65   626.1 1888.88   666.3 1895.71   699.6  1899.9
#Mann= 8 ,-1,0
       0      .1       0     250     .06       0     360     .05       0
   453.8    .045       0     463     .05       0  491.91      .1       0
  511.91     .05       0  621.91      .1       0
#XS Ineff= 2 , 0
          301.87 1899.68
Permanent Ineff=
       F       F
Bank Sta=453.8,463
XS Rating Curve= 0 ,0
Exp/Cntr(USF)=0,0
Exp/Cntr=0.3,0.1

Type RM Length L Ch R = 1 ,887     ,83.9,84,83
XS GIS Cut Line= 3
2186832.20925278640976.2068497882186964.28877312640721.398571613
2187348.83888101640439.706851245
#Sta/Elev= 30
       0 1912.73    82.3 1911.72      89 1909.07    97.2 1902.67   102.5 1895.64
     107 1887.74   111.5 1883.99   130.3 1883.81   134.1 1882.36   141.7 1874.96
   144.7 1873.56   173.8  1872.6   197.1 1872.92   209.9 1881.79   228.7 1882.93
   291.8 1882.14   315.7 1878.01   400.9  1875.6   429.5 1873.35   495.1 1873.14
   517.5 1875.02   524.3 1874.12   530.81874.156   564.9 1883.54   614.1 1886.33
   659.1  1886.9   673.4 1889.19   733.1 1892.13   747.7 1895.86   763.7 1895.41
#Mann= 9 ,-1,0
       0      .1       0     250     .07       0  387.01     .05       0
  477.01      .1       0   524.3    .045       0   530.8      .1       0
  637.01     .06       0  647.01      .1       0  757.01     .06       0
#XS Ineff= 2 , 0
          227.61 1891.83
Permanent Ineff=
       F       F
Bank Sta=524.3,530.8
XS Rating Curve= 0 ,0
Exp/Cntr(USF)=0,0
Exp/Cntr=0.3,0.1

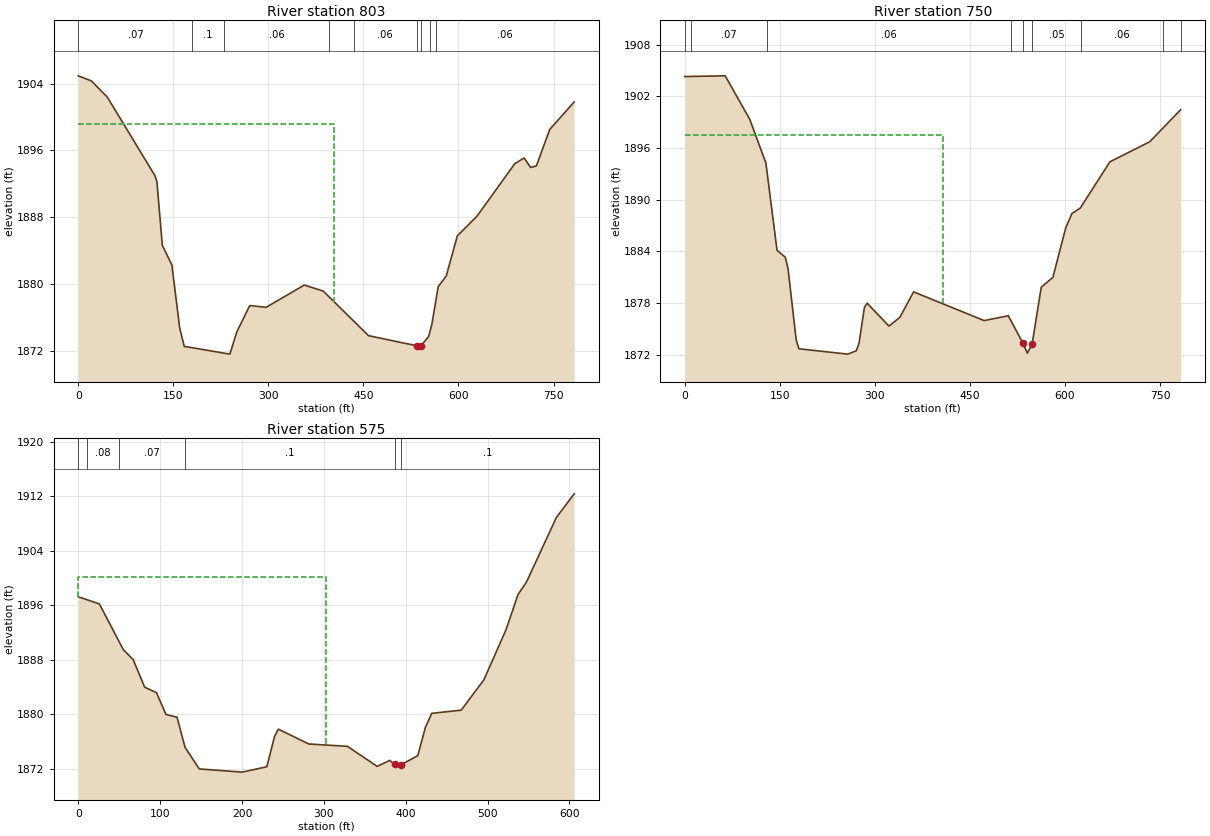
Type RM Length L Ch R = 1 ,803     ,52.4,52.6,53.5
XS GIS Cut Line= 3
2186959.14440096 641068.256779432187098.71895838640720.122538507
2187422.78862044640473.059528819
#Sta/Elev= 30
       0 1904.93    20.6 1904.32    45.8 1902.37     121 1892.95     124 1892.25
   132.6 1884.61   147.6 1882.28     160 1874.71   167.1  1872.5   239.2 1871.57
     250 1874.21   270.5 1877.39   296.4 1877.18   356.7 1879.85   386.5 1879.13
   458.1 1873.78  533.911872.578   540.9 1872.59   552.9 1873.67   558.1 1875.18
     568 1879.65   580.8 1880.95   598.2 1885.75   629.4 1888.12   688.8 1894.39
   703.6 1895.08   713.9 1893.95     723 1894.13   744.1 1898.51   782.6  1901.8
#Mann= 9 ,-1,0
       0     .07       0     180      .1       0     230     .06       0
  395.07     .05       0  435.07     .06       0  533.91    .045       0
   540.9     .06       0  555.07     .05       0  565.07     .06       0
#XS Ineff= 2 , 0
          403.96 1899.15
Permanent Ineff=
       F       F
Bank Sta=533.91,540.9
XS Rating Curve= 0 ,0
Exp/Cntr(USF)=0,0
Exp/Cntr=0.3,0.1

Type RM Length L Ch R = 1 ,750     ,174.8,175.8,173.5
XS GIS Cut Line= 3
2186996.84557452641104.3536477292187136.42013194640756.219406805
2187460.48979399640509.156397118
#Sta/Elev= 30
       0 1904.29    63.8 1904.37   102.5 1899.33     128 1894.26   145.6 1884.13
   158.6 1883.33   162.9 1882.03   175.8 1873.76   180.1 1872.71   257.2 1872.09
   270.6 1872.47   274.9 1873.32   283.5  1877.5   287.8    1878   322.3 1875.34
   339.6 1876.37   361.1 1879.31   472.5 1875.98   510.6 1876.54     534 1873.33
   540.7  1872.2   548.2 1873.25   562.6 1879.85     581 1880.99   601.1  1886.7
   611.1 1888.41   624.2 1889.03     671  1894.4   733.8 1896.72   782.6 1900.44
#Mann= 9 ,-1,0
       0     .06       0      10     .07       0     130     .06       0
  515.07     .05       0     534    .045       0   548.2     .05       0
  625.07     .06       0  755.07      .1       0  782.58     .06       0
#XS Ineff= 2 , 0
          407.48 1897.55
Permanent Ineff=
       F       F
Bank Sta=534,548.2
XS Rating Curve= 0 ,0
Exp/Cntr(USF)=0,0
Exp/Cntr=0.3,0.1

Type RM Length L Ch R = 1 ,575     ,,,
XS GIS Cut Line= 3
2187117.03420215641109.3915966252187256.75307614640882.044107171
2187516.80883103640664.684879046
#Sta/Elev= 30
       0 1897.21    25.7 1896.17    54.8 1889.48    67.1 1887.97      81 1883.95
    95.5 1883.13   107.1 1879.94   120.6 1879.53   130.4 1875.11   147.8 1871.94
   200.2 1871.47   230.3 1872.26   239.7 1876.69   244.4 1877.78   281.7  1875.6
   328.7 1875.26   365.1 1872.32   380.5 1873.19   386.3 1872.61   394.8 1872.58
   414.7 1873.89   424.1 1878.05   431.8  1880.1   467.8 1880.57   495.5 1885.02
   522.6 1892.39   537.2 1897.54   547.6 1899.39   584.1 1908.86   605.8 1912.33
#Mann= 6 ,-1,0
       0     .05       0      10     .08       0      50     .07       0
     130      .1       0   386.3    .045       0   394.8      .1       0
#XS Ineff= 2 , 0
          302.64 1900.05
Permanent Ineff=
       F       F
Bank Sta=386.3,394.8
XS Rating Curve= 0 ,0
Exp/Cntr(USF)=0,0
Exp/Cntr=0.3,0.1
LCMann Table=0

Chan Stop Cuts=-1
Use User Specified Reach Order=0
Composite Channel Slope=5